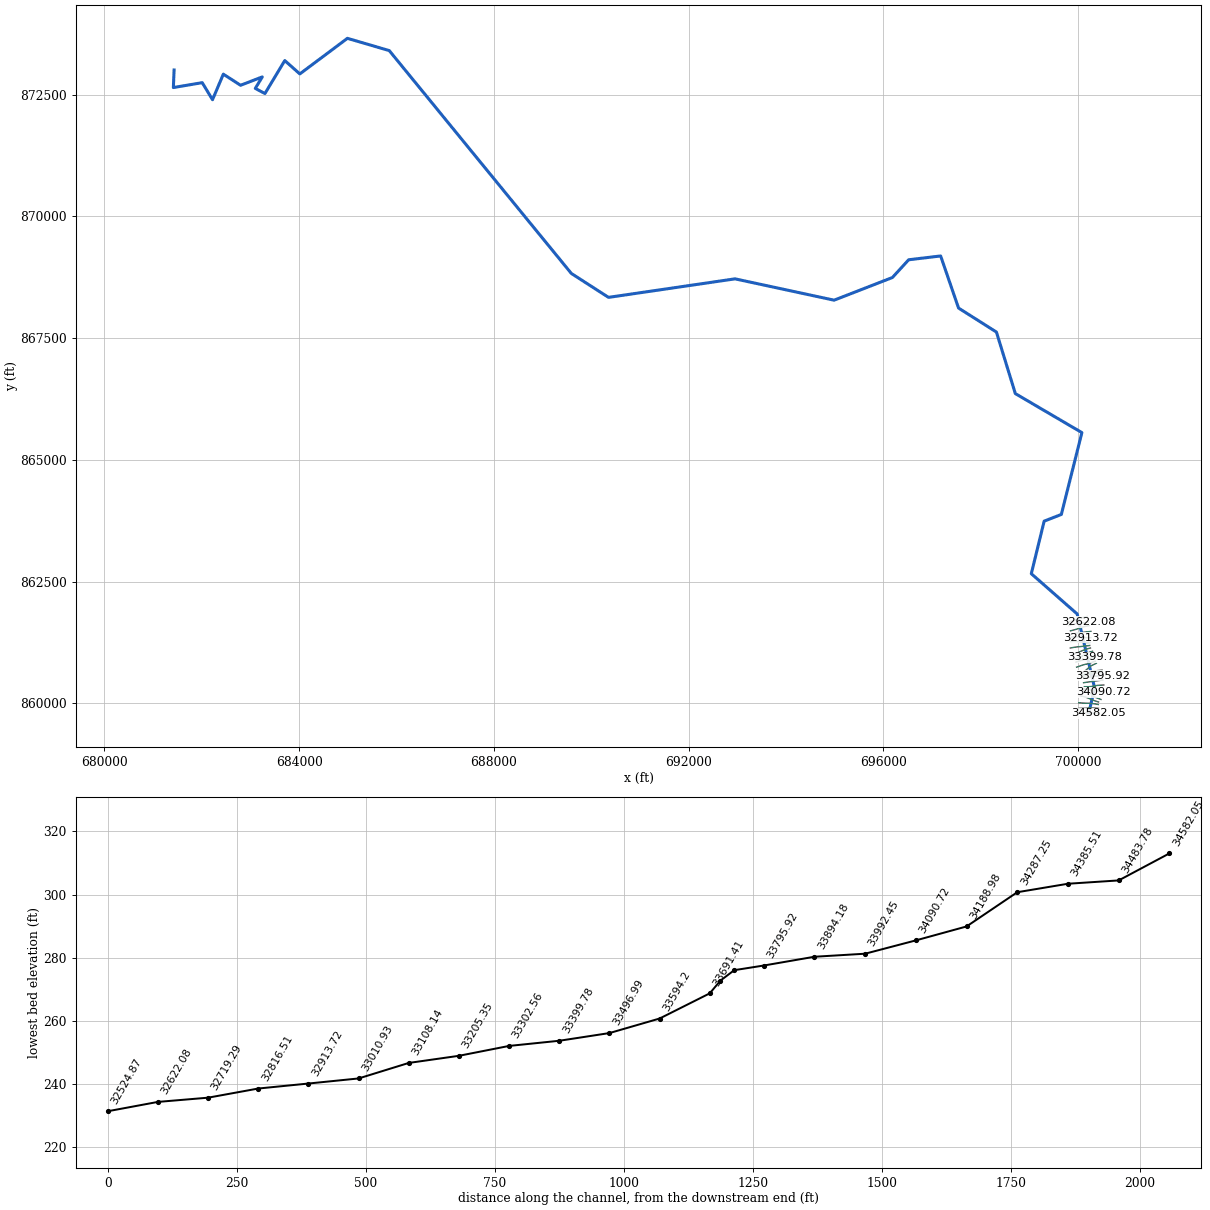
--- 13600_ras.prj (project) ---

Proj Title=13600
Current Plan=p01
Default Exp/Contr=0.3,0.1
English Units
Geom File=g01
Flow File=f01
Plan File=p01
Y Axis Title=Elevation
X Axis Title(PF)=Main Channel Distance
X Axis Title(XS)=Station
BEGIN DESCRIPTION:
RFD model 13600 exported to HEC-RAS
END DESCRIPTION:

--- 13600_ras.p01 (plan) ---

Plan Title=Plan 01
Program Version=4.10
Short Identifier=Plan 01
Geom File=g01
Flow File=f01
Subcritical Flow
Calc Critical at every XS
Secant Critical Depth

--- 13600_ras.f01 (steady flow) ---

Flow Title=Flow 01
Program Version=5.01
Number of Profiles= 6
Profile Names=10yr,25yr,50yr,100yr,100plus,500yr
River Rch & RM=13600,116,34582.05
     138  224.33  305.93  382.05   557.8 1014.79
River Rch & RM=13600,116, 33594.2
  141.13  229.45  312.93  390.82  570.59 1034.81
River Rch & RM=13600,116,33399.78
  150.07  244.03   332.9   415.8  607.06 1091.55
River Rch & RM=13600,116,33205.35
  154.68  251.57  343.22  428.71  625.92  1120.7
River Rch & RM=13600,116,33108.14
  156.21  254.07  346.64     433  632.17 1130.34
River Rch & RM=13600,116,33010.93
  159.65  259.68  354.33  442.62  646.22 1151.94
River Rch & RM=13600,116,32913.72
  161.57  262.81  358.61  447.96  654.02 1163.87
River Rch & RM=13600,116,32719.29
  168.08  273.42  373.11  466.06  680.45 1204.07
River Rch & RM=13600,116,32524.87
  170.37  277.14  378.19  472.42  689.73 1218.13
River Rch & RM=13600,116,32427.66
  173.41  282.09  384.96  480.87  702.07 1236.78
River Rch & RM=13600,116,32330.45
  176.81  287.64  392.54  490.34  715.89 1257.64
River Rch & RM=13600,116,32136.02
  363.69  593.07  811.16 1014.15 1480.66 2350.07
River Rch & RM=13600,116,32038.81
   408.5  666.59   912.2 1140.82  1665.6 2601.44
River Rch & RM=13600,116, 31941.6
   412.9  673.79  922.09  1153.2 1683.68  2625.7
River Rch & RM=13600,116,31844.39
  415.73  678.42  928.43 1161.15 1695.28 2641.25
River Rch & RM=13600,116,31747.17
  418.55  683.04  934.77 1169.08 1706.86 2656.76
River Rch & RM=13600,116,31455.54
  420.12   685.6  938.29 1173.49 1713.29 2665.36
River Rch & RM=13600,116,31358.33
  456.32  744.91 1019.74 1275.51 1862.24 2863.68
River Rch & RM=13600,116,31261.12
  458.47  748.43 1024.57 1281.56 1871.08 2875.37
River Rch & RM=13600,116, 31163.9
  460.62  751.95  1029.4 1287.61 1879.92 2887.04
River Rch & RM=13600,116,30918.43
  915.35  1503.5  2067.8 2594.65 3788.18 5302.51
River Rch & RM=13600,116,30672.96
  944.57 1551.65 2134.21 2678.05 3909.95 5448.71
River Rch & RM=13600,116,30427.49
  948.75 1558.53 2143.68 2689.94 3927.31 5469.47
River Rch & RM=13600,116,30182.02
  953.97 1567.11 2155.52 2704.79    3949 5495.38
River Rch & RM=13600,116,29936.55
  957.88 1573.55 2164.39 2715.92 3965.25 5514.78
River Rch & RM=13600,116,29691.08
  960.49 1577.83 2170.29 2723.34 3976.07 5527.69
River Rch & RM=13600,116,29445.61
  964.92 1585.12 2180.34 2735.94 3994.47 5549.62
River Rch & RM=13600,116,29200.14
  968.56 1591.12  2188.6 2746.31 4009.61 5567.66
River Rch & RM=13600,116,28954.67
  972.46 1597.54 2197.44 2757.41 4025.82 5586.96
River Rch & RM=13600,116,28709.64
   975.3 1602.22  2203.9 2765.52 4037.66 5601.09
River Rch & RM=13600,116,28464.62
  991.24  1628.5 2240.18 2811.12 4104.23 5680.51
River Rch & RM=13600,116,28219.59
  992.27 1630.19 2242.51 2814.05 4108.51 5685.62
River Rch & RM=13600,116,27974.56
  997.12  1638.2 2253.58 2827.96 4128.83 5709.86
River Rch & RM=13600,116,27729.54
  999.16 1641.57 2258.23 2833.82 4137.38 5720.05
River Rch & RM=13600,116,27484.51
 1049.57 1724.64 2372.82 2977.74  4347.5  5968.9
River Rch & RM=13600,116,27239.48
  1052.6 1729.64 2379.72 2986.43 4360.19 5983.93
River Rch & RM=13600,116,26994.46
 1085.92 1784.73 2455.89 3082.28 4500.14 6149.48
River Rch & RM=13600,116,26749.43
  1131.2 1859.47 2559.13  3212.1 4689.67 6372.02
River Rch & RM=13600,116, 26504.4
 1135.89 1867.23 2569.87 3225.62 4709.41 6395.21
River Rch & RM=13600,116,26259.37
  1151.4 1892.91  2605.4 3270.36 4774.73 6471.84
River Rch & RM=13600,116,26014.35
 1155.58 1899.82 2614.96 3282.41 4792.31 6492.46
River Rch & RM=13600,116,25769.32
 1193.69 1962.94 2702.33 3392.48 4953.02 6680.48
River Rch & RM=13600,116,25524.29
 1198.49 1970.92 2713.41 3406.46 4973.43 6704.43
River Rch & RM=13600,116,25279.27
 1205.69 1982.88 2730.01 3427.41 5004.03  6740.3
River Rch & RM=13600,116,25034.24
 1206.88 1984.88 2732.77  3430.9 5009.12 6746.27
River Rch & RM=13600,116,24789.21
 1223.31 2012.11 2770.51 3478.48 5078.57 6827.27
River Rch & RM=13600,116,24628.72
 1224.98 2014.89 2774.37 3483.35 5085.68 6835.58
River Rch & RM=13600,116,24525.21
 1232.86 2027.99 2792.54 3506.29 5119.18 6874.74
River Rch & RM=13600,116,24300.15
 1251.32 2058.63 2835.01 3559.85 5197.38 6965.76
River Rch & RM=13600,116,24075.08
 1252.98 2061.39 2838.84  3564.7 5204.46 6974.01
River Rch & RM=13600,116,23850.01
 1259.62 2072.44 2854.18 3584.06 5232.73 7006.97
River Rch & RM=13600,116,23624.95
 1267.91 2086.23 2873.32 3608.24 5268.03  7048.1
River Rch & RM=13600,116,23399.88
 1270.04 2089.77 2878.24 3614.45  5277.1 7058.66
River Rch & RM=13600,116,23174.82
 2059.37 3393.45  4680.2 5880.19 8585.0810726.26
River Rch & RM=13600,116,22949.75
 2416.79 3989.67 5509.83 6929.2610116.7212374.69
River Rch & RM=13600,116,22801.23
 2417.81 3991.38 5512.21 6932.2810121.12 12379.4
River Rch & RM=13600,116,22673.07
 2418.82 3993.08 5514.59 6935.2910125.52 12384.1
River Rch & RM=13600,116,22455.18
 2421.26 3997.16 5520.28  6942.510136.0512395.38
River Rch & RM=13600,116,22194.54
 2426.09 4005.28 5531.62  6956.910157.0712417.94
River Rch & RM=13600,116,21470.99
 2542.24 4199.13 5801.48 7298.2110655.3912946.28
River Rch & RM=13600,116,21161.14
 2545.86 4205.18 5809.94 7308.9310671.0412962.91
River Rch & RM=13600,116,20489.28
  2564.1 4235.76 5852.62 7363.0510750.0513046.87
River Rch & RM=13600,116,20253.86
 2625.29 4339.04 5997.42 7547.3711019.1613334.96
River Rch & RM=13600,116,20018.44
 2626.45    4341 6000.17 7550.8711024.2713340.45
River Rch & RM=13600,116,19783.02
 2628.57 4344.58 6005.21 7557.2911033.6413350.49
River Rch & RM=13600,116, 19547.6
 2693.63 4453.97 6158.21 7751.6211317.3713651.43
River Rch & RM=13600,116,19312.18
 2700.92  4466.3 6175.52 7773.6811349.5813685.81
River Rch & RM=13600,116,19076.76
 2702.26 4468.56  6178.7 7777.74 11355.513692.14
River Rch & RM=13600,116,18841.35
 2705.89 4474.72 6187.35 7788.7611371.5913709.31
River Rch & RM=13600,116,18605.93
 2708.95  4479.9 6194.62 7798.0311385.1313723.77
River Rch & RM=13600,116,18370.51
 2843.57 4707.57 6514.29 8205.41 11979.914355.87
River Rch & RM=13600,116,17819.51
 2876.98 4764.04 6593.55 8306.3912127.3314511.74
River Rch & RM=13600,116,17627.38
 2888.74 4784.09 6621.85 8342.6212180.2314568.25
River Rch & RM=13600,116,17435.26
 2891.31 4788.48 6628.04 8350.5412191.7914580.61
River Rch & RM=13600,116,17243.13
 2893.34 4791.93 6632.91 8356.7712200.8914590.31
River Rch & RM=13600,116,17051.01
 2896.08 4796.61 6639.52 8365.2412213.2514603.53
River Rch & RM=13600,116,16667.01
 2959.81 4905.09 6792.46 8560.8612498.8514907.32
River Rch & RM=13600,116,16427.65
  2961.4 4907.83 6796.35 8565.8612506.1614915.19
River Rch & RM=13600,116,16188.29
 2972.54 4926.91 6823.35 8600.5112556.7514969.35
River Rch & RM=13600,116,15948.93
 2975.37 4931.78 6830.25  8609.412569.7214983.32
River Rch & RM=13600,116,15709.56
 2977.49 4935.43 6835.44 8616.0712579.4614993.79
River Rch & RM=13600,116, 15470.2
 2978.73 4937.56 6838.46 8619.9512585.13 14999.9
River Rch & RM=13600,116,15230.84
 3017.36 5004.11    6933 8741.6812762.8615191.34
River Rch & RM=13600,116,14991.48
 3021.28 5010.93 6942.73 8754.2512781.2115211.29
River Rch & RM=13600,116,14752.12
 3022.64 5013.29  6946.1 8758.6312787.5915218.23
River Rch & RM=13600,116,14512.76
 3161.32 5249.51 7279.31 9184.9813410.0815875.41
River Rch & RM=13600,116, 14273.4
 3172.44 5268.84 7306.91 9220.6813462.1915931.67
River Rch & RM=13600,116,13797.02
 3207.31 5329.56 7393.75 9333.1413626.3916109.34
River Rch & RM=13600,116,12967.56
 3217.85 5347.98 7420.15 9367.3913676.3916163.59
River Rch & RM=13600,116, 12138.1
 3312.95 5512.14 7653.65 9668.3814115.8416631.94
River Rch & RM=13600,116,11308.65
 3346.56 5570.47 7736.89 9775.9814272.9216799.97
River Rch & RM=13600,116,10479.19
 3676.37 6131.42 8527.59 10786.915748.8818324.37
River Rch & RM=13600,116,9649.729
 3684.15 6145.04 8547.1310812.2815785.9418363.87
River Rch & RM=13600,116,8313.988
 3725.74 6217.74 8651.3510947.5415983.4118573.69
River Rch & RM=13600,116,7870.277
 3730.11 6225.33 8662.21 10961.616003.9318595.34
River Rch & RM=13600,116,6852.267
 3846.21 6426.92 8950.0711333.8716547.4519165.97
River Rch & RM=13600,116,5753.477
 3860.58 6452.04 8986.08 11380.616615.6819238.01
River Rch & RM=13600,116,    4281
 3861.84 6454.24 8989.23 11384.716621.6619244.34
Boundary for River Rch & Prof#=13600,116,1
Up Type= 0
Dn Type= 2
Boundary for River Rch & Prof#=13600,116,2
Up Type= 0
Dn Type= 2
Boundary for River Rch & Prof#=13600,116,2
Up Type= 0
Dn Type= 2
Boundary for River Rch & Prof#=13600,116,2
Up Type= 0
Dn Type= 2
Boundary for River Rch & Prof#=13600,116,2
Up Type= 0
Dn Type= 2
Boundary for River Rch & Prof#=13600,116,2
Up Type= 0
Dn Type= 2

--- 13600_ras.g01 (geometry) ---

Geom Title=13600
Program Version=4.10

River Reach=13600,116
Reach XY= 30
700217.241445482859805.233167112700336.019065529860315.907456756
699978.392644584861836.330704272699035.863020957 862663.15719527
699299.918247104863742.424419016699652.728972018863879.868908912
700074.614267558865560.392944053698708.043350458866361.745432213
698319.434930027867625.464717701697541.790214598868118.218430802
 697174.19487834 869188.20475702696517.630635679869109.864705354
696183.752796412868745.521290407694986.369150519868280.135382921
692951.914791495868718.164446995690353.636410832868337.655624568
689589.787361354868829.587215945685851.535639018873405.369684249
684992.160638988873657.105795383684014.768964469872926.244845092
  683705.7197164873200.476208195683298.248245448872523.325126782
683100.765606523872628.576862812683243.994773209872865.122001767
682798.138327092872693.336822048682444.298592657872921.545612887
 682221.98456338872396.394090638682010.584226757872746.896973252
681417.979156554872646.543371618681433.013870418873007.266098976

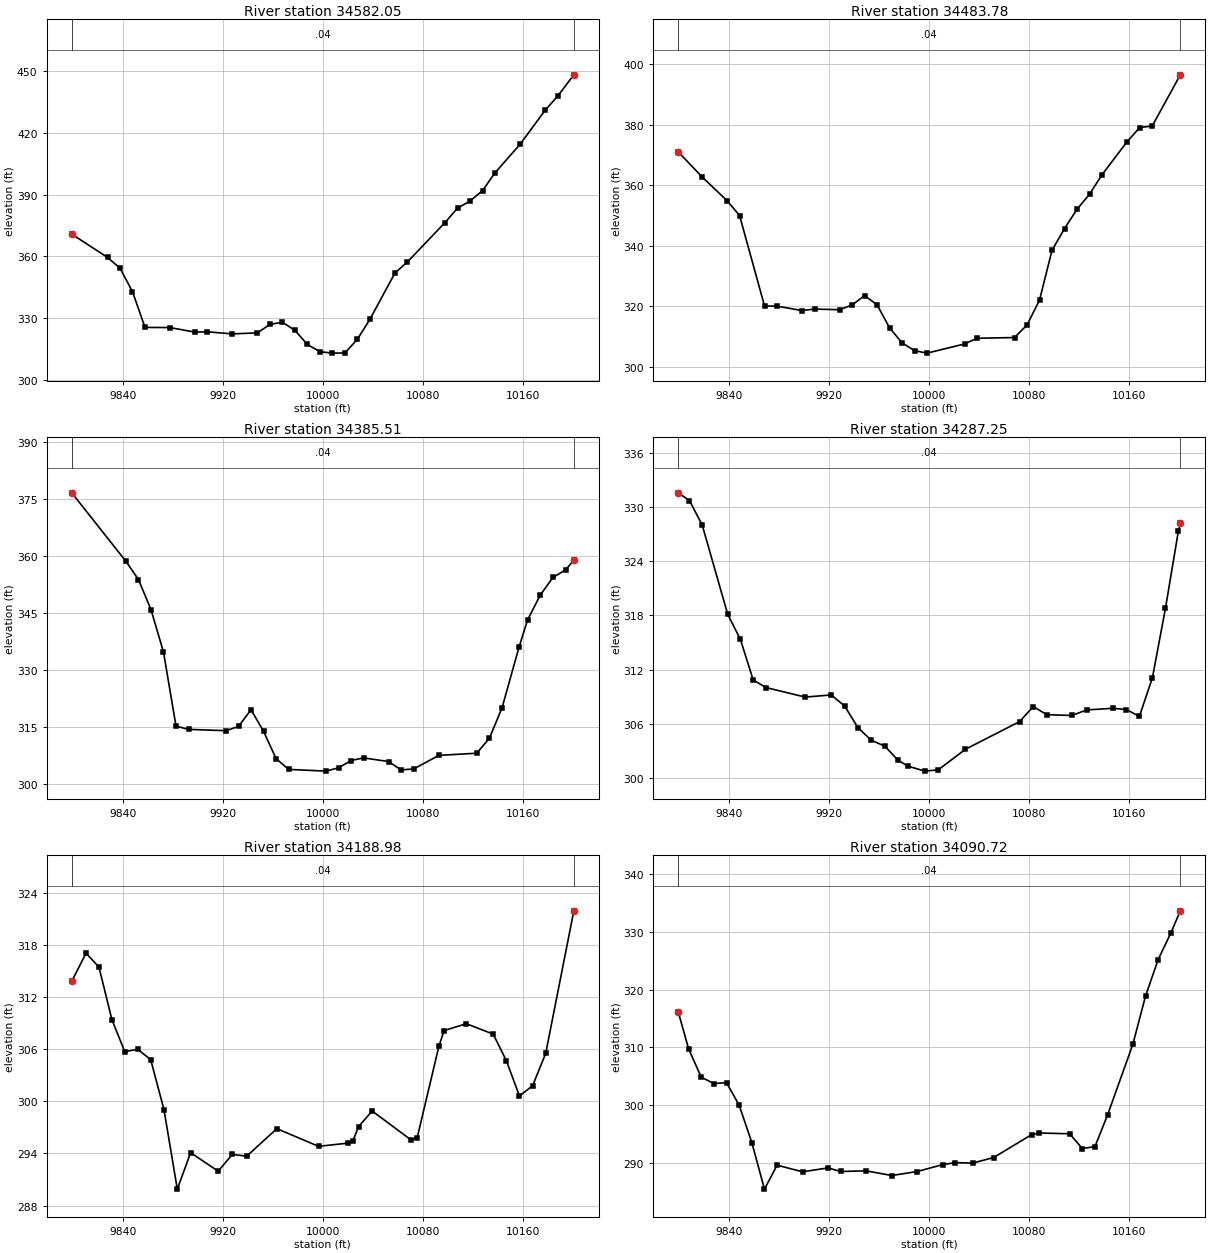
Type RM Length L Ch R = 1 ,34582.05,98.266000,98.266000,98.266000
XS GIS Cut Line= 5
700016.383441064859808.710717713700179.528507422859808.258250729
700216.316589055859806.303045885700218.311324255859806.158023539
700417.998721868859795.086677787
#Sta/Elev= 30
9799.014370.76529827.631359.48129837.631354.24259847.631342.86119857.631325.5042
9877.631325.43179897.631323.22449907.631323.36869927.631322.36359947.631322.8666
9957.631326.94829967.639328.03769977.653 324.1089987.667317.21639997.682313.7275
 10007.7313.028410017.71313.093710027.73319.801310037.75329.482310057.78 351.947
10067.79357.295110097.84376.391410107.85383.424110117.87386.797910127.88391.9079
 10137.9400.563810157.93414.375510177.96430.846210187.98437.720710200.99448.0895
#Mann= 3 , 0 , 0
9799.014    0.04       09799.014    0.04       010200.99    0.04       0
#XS Ineff= 2 , 0
       0                               0
Bank Sta=9799.014,10200.99
Exp/Cntr=0.3,0.1

Type RM Length L Ch R = 1 ,34483.78,98.266100,98.266100,98.266100
XS GIS Cut Line= 6
700015.899197089 859899.47844182700136.915756199859900.559320169
700217.794176609859904.408447181700283.016097506859906.537489912
700344.885092085859904.263271707700417.390457358859897.661949852
#Sta/Elev= 30
9799.009371.0438 9818.11362.74649838.111354.88259848.111349.97749868.112320.0416
9878.112320.02159898.113318.54899908.114319.04699928.123318.83099938.134320.3732
9948.146323.48589958.157320.49239968.168312.86129978.179307.8769 9988.19305.2897
9998.201304.474810028.22 307.50810038.23309.392710068.24309.629510078.25313.7759
10088.26 322.02210098.26338.494510108.27  345.6710118.28352.070510128.28357.0288
10138.32 363.50110158.41374.423410168.45 379.06410178.49379.599110200.97396.5113
#Mann= 3 , 0 , 0
9799.009    0.04       09799.009    0.04       010200.97    0.04       0
#XS Ineff= 2 , 0
       0                10058.81       0
Bank Sta=9799.009,10200.97
Exp/Cntr=0.3,0.1

Type RM Length L Ch R = 1 ,34385.51,98.266000,98.266000,98.266000
XS GIS Cut Line= 6
700011.695135745860012.130273095700139.844135092860004.681854802
700211.442931681860002.540459704700272.690957903859999.532152873
700328.492745496859992.207249685700411.513786507 859977.17342468
#Sta/Elev= 30
9799.004376.54229842.382 358.5339852.399353.75479862.416345.86529872.432334.7269
9882.449 315.2459892.466314.39339922.517314.04759932.527315.17039942.532319.5459
9952.536313.88859962.541306.73369972.545303.875610002.56303.421810012.57304.2966
10022.59306.2021 10032.6306.899210052.62305.938310062.65303.745110072.74303.9897
10092.91307.560610123.22308.124610133.38312.088610143.54320.113110157.05335.9566
10163.87343.104210174.03349.654210184.19354.297210194.35356.303610200.97 358.843
#Mann= 3 , 0 , 0
9799.004    0.04       09799.004    0.04       010200.97    0.04       0
#XS Ineff= 2 , 0
       0                10039.04       0
Bank Sta=9799.004,10200.97
Exp/Cntr=0.3,0.1

Type RM Length L Ch R = 1 ,34287.25,98.266100,98.266100,98.266100
XS GIS Cut Line= 6
700036.156981653860156.020137509700095.934965609860144.148849372
700154.079343858860127.302549295700232.397199155860097.293909598
700325.556252963860057.791210757700416.438132571860028.929155271
#Sta/Elev= 30
9799.049331.57919808.065330.7165 9818.26328.0044 9838.65318.11349848.846315.3273
9859.041310.84239869.432309.99449900.666308.94429921.516309.17889932.225307.9601
9942.933305.54989953.642304.15069964.351303.5117 9975.06301.94119982.868301.2956
9996.477300.737810007.23300.882310028.95303.1597 10072.4306.232710083.26307.8961
10094.12306.993210114.06306.904410126.18307.523110147.36307.703810157.83307.5582
10168.24306.809410178.66311.090110189.07318.767110199.48327.379910200.98328.1862
#Mann= 3 , 0 , 0
9799.049    0.04       09799.049    0.04       010200.98    0.04       0
#XS Ineff= 2 , 0
       09950.602        10038.73       0
Bank Sta=9799.049,10200.98
Exp/Cntr=0.3,0.1

Type RM Length L Ch R = 1 ,34188.98,98.266000,98.266000,98.266000
XS GIS Cut Line= 6
700113.892511702860258.550338852700228.452607927860220.735129951
700269.372311129860194.804298942700311.142305556860151.695739328
700347.115696376860126.285367972700466.441453972860080.383140544
#Sta/Elev= 30
9799.083313.84339810.545317.06979820.864315.45399831.184309.41999841.503305.7174
9851.822305.99959862.239304.80929872.893 299.0359883.547289.89549894.211294.0902
9916.255291.96289927.588293.89429939.085293.68849963.206296.85879996.612294.8214
10019.77295.186610024.07295.451210028.65297.099510039.48298.889210070.24295.6016
10075.51295.802510092.95306.374510097.06308.154210114.88 308.94110136.36307.7457
10146.87304.689110157.37300.621810167.88301.796510178.38305.5281 10200.9 321.941
#Mann= 3 , 0 , 0
9799.083    0.04       09799.083    0.04       0 10200.9    0.04       0
#XS Ineff= 2 , 0
       09948.626        10026.23       0
Bank Sta=9799.083,10200.9
Exp/Cntr=0.3,0.1

Type RM Length L Ch R = 1 ,34090.72,98.266100,98.266100,98.266100
XS GIS Cut Line= 6
700126.782885397860297.657972345 700210.14626247860284.742228839
700323.486187595860261.875943478700325.442293482860261.459230435
700405.604751781860245.852447846700522.533440111860227.777298055
#Sta/Elev= 30
9799.018316.14069807.334309.72799817.453304.83279827.572303.73859837.692 303.893
9847.811299.9827 9857.93 293.5419868.049285.48379878.169289.62549898.529288.4778
9918.932289.15189929.134288.53379949.537288.6466 9969.94287.83689990.343288.5278
10010.74289.720510020.92290.0622 10034.8 289.98910051.49290.939910082.05 294.923
10088.25295.189810112.41295.050710122.53292.499510132.65292.835110142.77 298.323
10163.01310.534910173.12318.845110183.24325.173810193.36329.738510200.99333.6028
#Mann= 3 , 0 , 0
9799.018    0.04       09799.018    0.04       010200.99    0.04       0
#XS Ineff= 2 , 0
       09951.898         10026.4       0
Bank Sta=9799.018,10200.99
Exp/Cntr=0.3,0.1

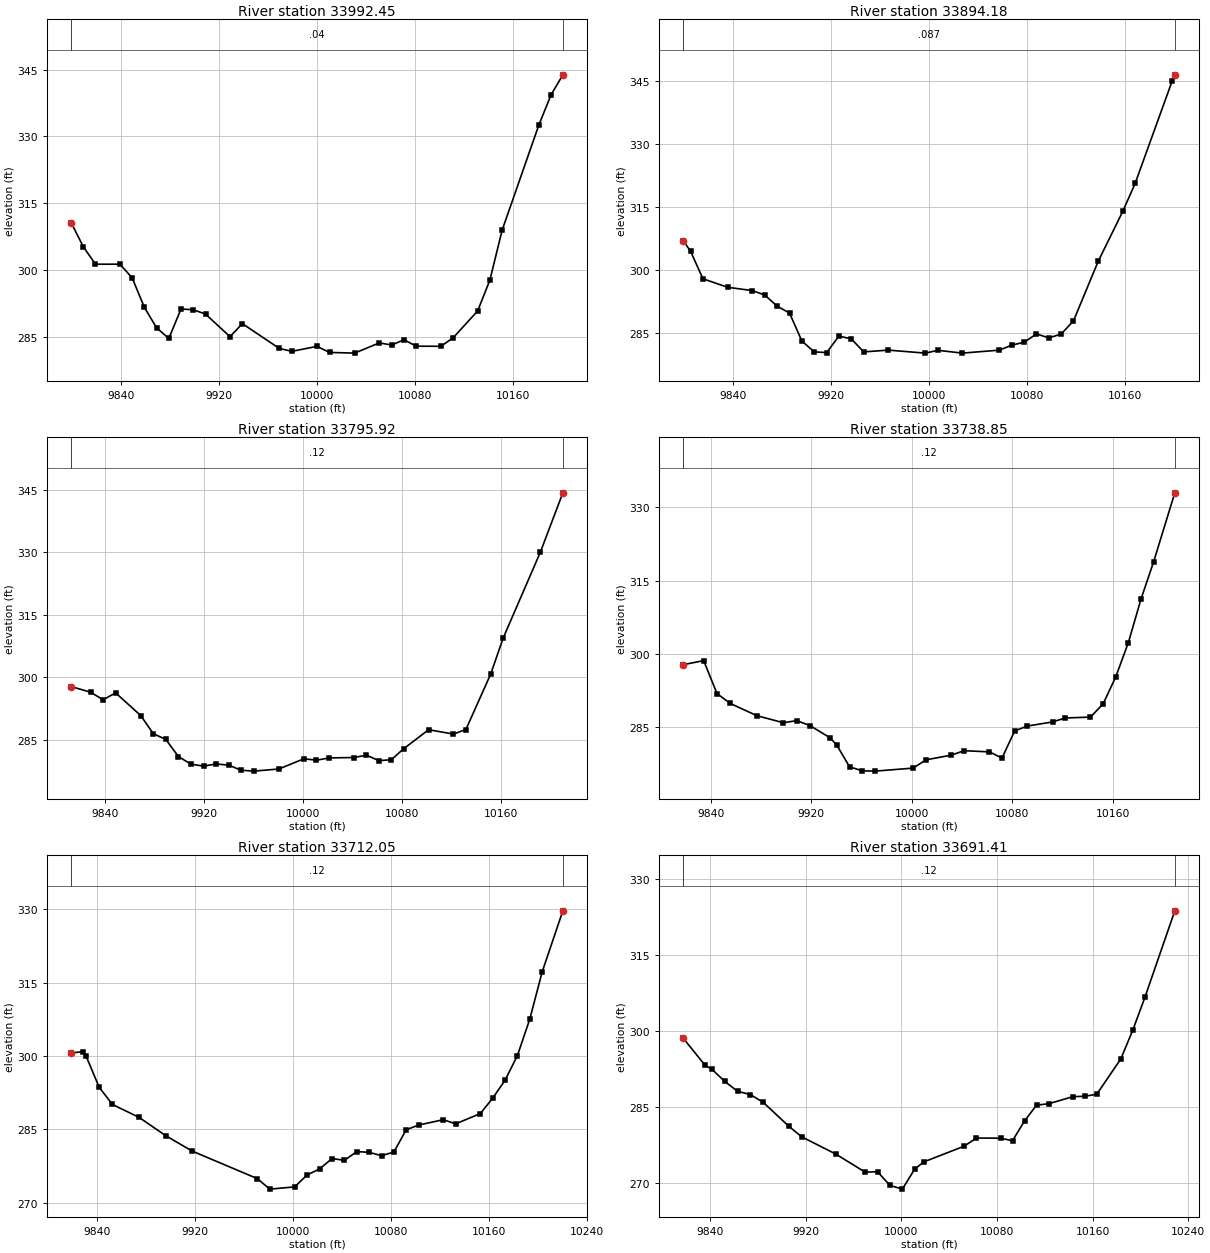
Type RM Length L Ch R = 1 ,33992.45,98.266000,98.266000,98.266000
XS GIS Cut Line= 6
700125.230342826860343.765676054700209.600513547860343.465349465
700259.891757607860345.860651438700294.412483949860350.330734602
700387.954786411860369.136174333700524.575576431860378.083938568
#Sta/Elev= 30
9799.034310.56689808.804 305.2429818.804301.26199838.804301.26889848.804298.2059
9858.804 291.5749868.804286.95989878.804284.5705 9888.81291.20189898.821291.0167
9908.833290.05089928.855284.95969938.904287.90219969.164 282.3229979.416281.6677
9999.928282.786510010.21281.428610030.66281.267210050.91283.562710061.04283.0947
10071.11284.268110081.15 282.82710101.23282.803610111.27284.713910131.32290.7528
10141.33297.709210151.34308.926410181.38332.589410191.39339.383310200.98 343.853
#Mann= 3 , 0 , 0
9799.034    0.04       09799.034    0.04       010200.98    0.04       0
#XS Ineff= 2 , 0
       09945.867        10025.12       0
Bank Sta=9799.034,10200.98
Exp/Cntr=0.3,0.1

Type RM Length L Ch R = 1 ,33894.18,98.266100,98.266100,98.266100
XS GIS Cut Line= 5
700109.029317549860424.733474505700276.706566381860449.870133355
700306.905600161860453.748725272700308.893096313860453.972016666
700507.140842551860480.345510289
#Sta/Elev= 30
9799.002 307.0959805.039304.54679815.151298.00459835.375295.97829855.598295.1879
 9865.71294.13559875.822291.47579885.933289.85699896.045283.18249906.157280.5965
9916.269280.4353 9926.38 284.3579936.492283.68779946.604280.59689966.827281.0153
9997.079280.301810007.16280.970410027.34280.3098 10057.6281.010310067.69282.2118
10077.78282.880510087.87 284.87210097.95 283.92910108.04284.839110118.13287.9723
10138.31302.140710158.48314.082210168.57320.718510198.83345.105810200.99346.5646
#Mann= 3 , 0 , 0
9799.002   0.087       09799.002   0.087       010200.99   0.087       0
#XS Ineff= 2 , 0
       09930.648        10041.42       0
Bank Sta=9799.002,10200.99
Exp/Cntr=0.3,0.1

Type RM Length L Ch R = 1 ,33795.92,57.073000,57.073000,57.073000
XS GIS Cut Line= 3
700109.595745564860520.860499352700326.908236146860556.454786599
700503.006288856860571.441854924
#Sta/Elev= 30
9812.634297.82129828.243296.45559838.377 294.656 9848.51296.30569868.776290.8384
 9878.91286.50079889.043285.11589899.176281.01579909.309279.19499919.443278.7205
9929.576279.24129939.709278.96499949.842277.73039959.976277.52069980.242 278.029
10000.51280.488410010.64280.138410020.78280.690710040.96280.7856   10051281.3511
10061.04280.031510071.07280.261710081.11282.905910101.18287.459810121.25 286.418
10131.29287.507510151.36300.8477 10161.4309.468410191.51330.141410209.58344.3188
#Mann= 3 , 0 , 0
9812.634    0.12       09812.634    0.12       010209.58    0.12       0
#XS Ineff= 2 , 0
       0                 10052.1       0
Bank Sta=9812.634,10209.58
Exp/Cntr=0.3,0.1

Type RM Length L Ch R = 1 ,33738.85,26.797700,26.797700,26.797700
XS GIS Cut Line= 4
700109.595745564860556.454786599700227.618908554860597.669224456
700326.908236146860614.529676318700491.765987635860633.263511717
#Sta/Elev= 30
9817.912297.81689834.229298.64749844.821291.91839855.413289.89499876.597287.3884
9897.782285.94819908.374286.38069918.966285.36069934.828282.87949940.151281.4279
9950.411 276.9459960.555276.12169970.698276.052710001.13 276.67210011.27278.3576
10031.56279.3279 10041.7280.231310061.84279.988510071.91278.725610081.97284.2746
10092.04285.267710112.17286.111810122.23286.921110142.36287.101610152.42289.7958
10162.49295.311410172.55302.345210182.62311.233310192.68318.865910209.55332.9634
#Mann= 3 , 0 , 0
9817.912    0.12       09817.912    0.12       010209.55    0.12       0
#XS Ineff= 2 , 0
       0                10078.44       0
Bank Sta=9817.912,10209.55
Exp/Cntr=0.3,0.1

Type RM Length L Ch R = 1 ,33712.05,20.635300,20.635300,20.635300
XS GIS Cut Line= 4
700103.975594997860571.441854924700229.492292106860623.896594033
700313.794551402860638.883662328700491.765987635860661.364264816
#Sta/Elev= 30
9819.001300.62589828.229300.88269830.949300.08269841.788293.59779852.626290.0744
9874.302287.44379895.978 283.7079917.654280.53529970.788274.90499980.945272.7511
10001.26 273.20910011.42275.650910021.57276.876810031.73 279.01310041.88278.6458
10051.96280.434810062.04280.281910072.12279.590810082.19280.344610092.27284.9099
10102.35285.860810122.51286.966510132.59286.110210152.75 288.22210162.83291.3773
10172.91295.046710182.99300.093310193.07307.542910203.15317.202610220.05329.7163
#Mann= 3 , 0 , 0
9819.001    0.12       09819.001    0.12       010220.05    0.12       0
#XS Ineff= 2 , 0
       0                10097.46       0
Bank Sta=9819.001,10220.05
Exp/Cntr=0.3,0.1

Type RM Length L Ch R = 1 ,33691.41,97.211900,97.211900,97.211900
XS GIS Cut Line= 4
700092.735293746860588.302306771700216.378607303860637.010278806
700319.414701968 860665.11103189700489.892604053860683.844867289
#Sta/Elev= 30
9817.544298.54089835.818 293.2019841.475292.41499852.222290.0152 9862.97288.0506
9873.718287.40399884.466285.87059905.962281.1162 9916.71279.04399944.951 275.672
9969.737272.07279980.103272.14949990.468269.458610000.83268.7157 10011.2272.6785
10018.81274.100510052.66277.210210062.85278.819410082.97278.771310093.03278.2901
10103.09282.205510113.16285.316310123.22285.584710143.34286.9794 10153.4287.0646
10163.46287.463710183.58294.445710193.64300.1578 10203.7306.594110228.74323.7071
#Mann= 3 , 0 , 0
9817.544    0.12       09817.544    0.12       010228.74    0.12       0
#XS Ineff= 2 , 0
       0                10125.45       0
Bank Sta=9817.544,10228.74
Exp/Cntr=0.3,0.1

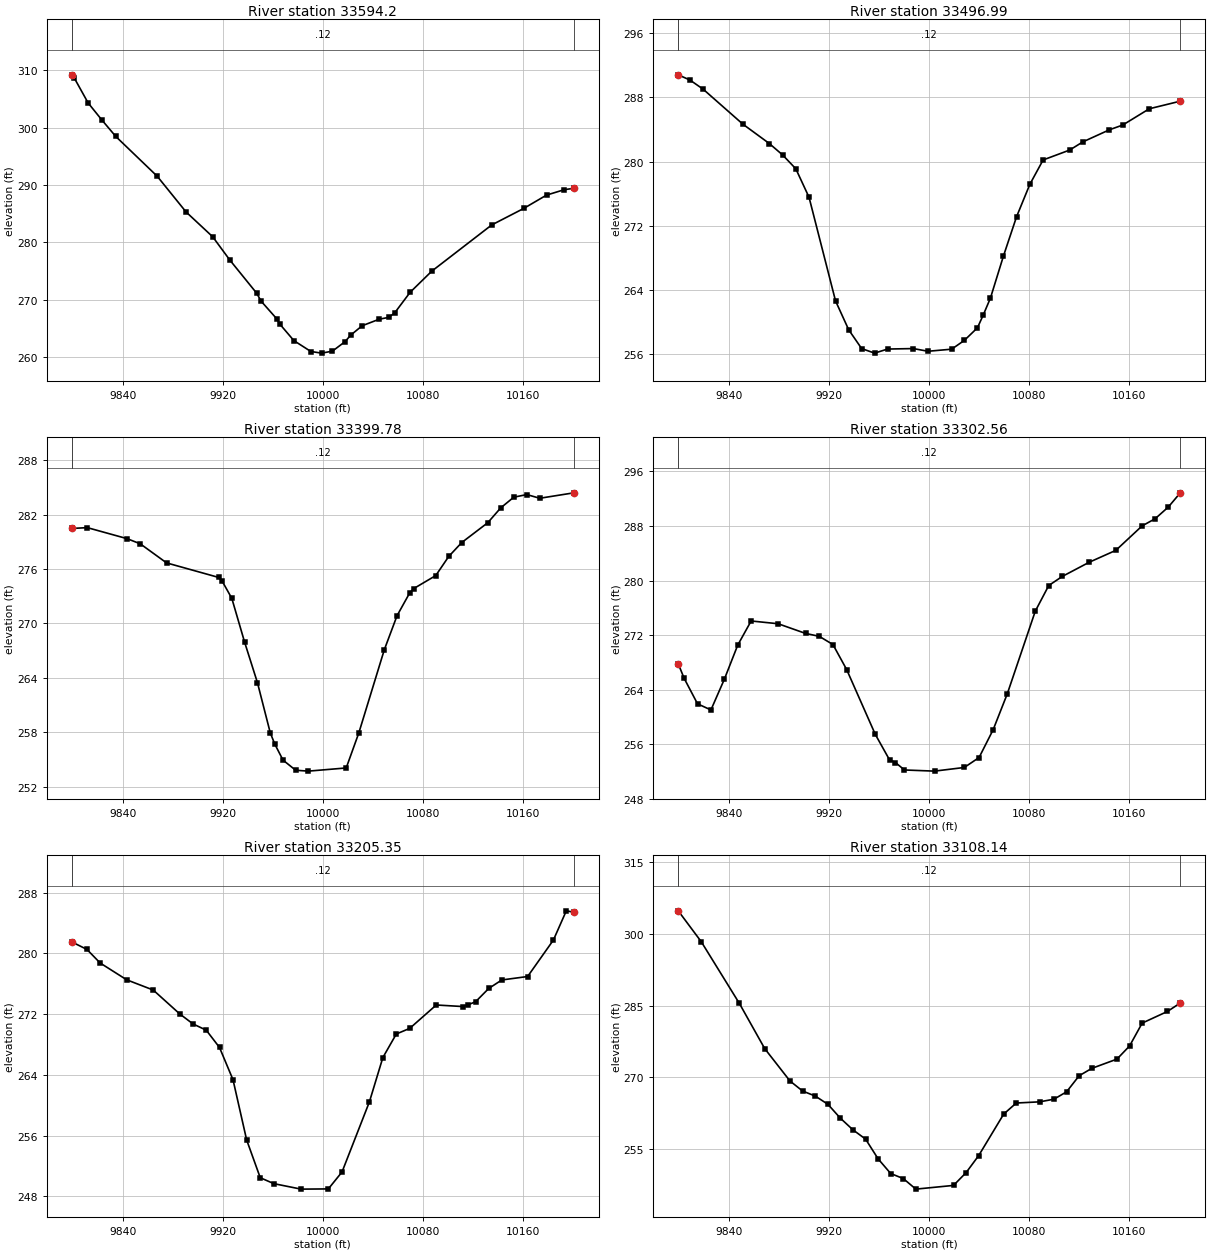
Type RM Length L Ch R = 1 , 33594.2,97.211800,97.211800,97.211800
XS GIS Cut Line= 6
 700033.11612556860613.449251111700099.022730532860644.358205025
700146.441871106860672.927332206700235.292834463860750.918543274
  700268.9059184860774.784452205700371.939987168860823.600141275
#Sta/Elev= 30
9799.079309.16539801.159308.58329812.205304.2612 9823.25301.28669834.295298.4432
 9867.43291.52469890.526285.31049911.872280.9852 9925.55276.94499946.931271.2037
 9950.72269.75589963.247266.68289965.512265.80889976.828262.92159990.442261.0235
    9999260.740410007.66261.081910017.75262.727310022.29263.863810031.46265.4997
10045.16266.644910052.61 266.95410057.47267.729510069.89271.326210087.24275.0077
10135.16283.041510160.73285.908810179.06288.239710193.36 289.18610200.91289.4155
#Mann= 3 , 0 , 0
9799.079    0.12       09799.079    0.12       010200.91    0.12       0
#XS Ineff= 2 , 0
       0                               0
Bank Sta=9799.079,10200.91
Exp/Cntr=0.3,0.1

Type RM Length L Ch R = 1 ,33496.99,97.211900,97.211900,97.211900
XS GIS Cut Line= 6
699966.143811645860743.970713674700093.302051136860788.446048057
700134.165473821860799.708470871 700185.49700402860810.926113527
700221.573088377860821.461132124700348.380171114860866.965910381
#Sta/Elev= 30
9799.029290.82219808.411290.17259819.005289.02789850.787284.67169871.976282.2563
 9882.57280.84019893.164279.11059903.758275.55529924.946262.65179935.502259.0458
9945.875256.70119956.248256.13639966.621256.64479987.211256.7043    9999 256.369
10017.92256.627810028.16257.732510038.57 259.29610043.21260.885710048.99263.0068
10059.41268.2507 10069.9273.141510080.52 277.17610091.15280.212610112.39281.4458
10123.02282.468910144.27283.975410154.89284.564110176.14286.591610200.98287.5404
#Mann= 3 , 0 , 0
9799.029    0.12       09799.029    0.12       010200.98    0.12       0
#XS Ineff= 2 , 0
       0                               0
Bank Sta=9799.029,10200.98
Exp/Cntr=0.3,0.1

Type RM Length L Ch R = 1 ,33399.78,97.211800,97.211800,97.211800
XS GIS Cut Line= 6
  699953.2045101860847.593311239700075.069277583860887.308359144
700112.389298674860895.887614769700177.573289123860905.805973988
700218.059677902 860914.16158422700341.188283421 860949.80501323
#Sta/Elev= 30
9799.022280.46759811.496280.55579843.224279.34399853.799278.77679874.922276.6672
9916.701 275.0619919.223274.70199927.146272.75919937.408267.91679947.669263.4552
9957.929257.9248 9961.55256.68079968.154254.91169978.275253.79579988.396253.6994
10018.73254.049110028.84257.919110049.24267.092110059.45 270.84910069.66273.3807
10072.79273.835710090.42275.269410100.83277.381610111.24278.914810132.06281.0994
10142.47282.740810152.89283.9156 10163.3284.202810173.71283.797710200.97284.3962
#Mann= 3 , 0 , 0
9799.022    0.12       09799.022    0.12       010200.97    0.12       0
#XS Ineff= 2 , 0
       0                               0
Bank Sta=9799.022,10200.97
Exp/Cntr=0.3,0.1

Type RM Length L Ch R = 1 ,33302.56,97.211900,97.211900,97.211900
XS GIS Cut Line= 6
699930.602892095860903.919364356700054.911377524860955.706883866
 700143.21520269861010.692258694700180.472211784 861030.33103712
 700236.91096187861053.237626489700294.159919258861071.472828176
#Sta/Elev= 30
9799.034267.79589803.751265.66979814.478261.92859825.205261.03039835.932265.5251
9846.659270.52969857.385274.06979878.986273.66519900.929272.24799911.901271.8213
9922.873 270.6179933.849266.95259956.783257.4479 9968.25253.6903 9972.95253.3184
9980.123252.233210004.17252.064210028.03252.600110039.85254.056610051.16258.1508
10062.46 263.40510084.84275.504710095.63279.267410106.42280.593210128.01282.6761
10149.35284.422610170.34288.001110180.83289.060110191.33290.766410200.94292.8505
#Mann= 3 , 0 , 0
9799.034    0.12       09799.034    0.12       010200.94    0.12       0
#XS Ineff= 2 , 0
       0                               0
Bank Sta=9799.034,10200.94
Exp/Cntr=0.3,0.1

Type RM Length L Ch R = 1 ,33205.35,97.211900,97.211900,97.211900
XS GIS Cut Line= 6
 699873.57879678861000.492925521699987.762484905861041.144059674
700095.481906775861088.328851097700134.659088257861103.816979334
 700192.64946672861122.469872428700250.850413543861137.420793187
#Sta/Elev= 30
9799.031281.52539811.155280.5382 9821.77278.74359842.999276.53039864.229275.1833
9885.459272.03539896.073270.71489906.688  269.899917.303267.6121 9928.12263.3523
9939.015255.42759949.909250.44069960.803249.65759982.592248.935910004.43248.9645
10015.39251.200410037.31260.442710048.07266.280410058.83269.385810069.58270.1265
10090.83273.210110111.84273.007810116.49273.245710122.34273.643510132.85275.3911
10143.31276.511110163.96276.962210184.61281.773810194.93285.623710200.97285.4412
#Mann= 3 , 0 , 0
9799.031    0.12       09799.031    0.12       010200.97    0.12       0
#XS Ineff= 2 , 0
       0                               0
Bank Sta=9799.031,10200.97
Exp/Cntr=0.3,0.1

Type RM Length L Ch R = 1 ,33108.14,97.211800,97.211800,97.211800
XS GIS Cut Line= 6
699836.862340738861137.433616901699896.713542175 861148.56666305
699956.636838272861157.508607092700034.690298873861166.097458824
700131.761596903861175.814734026700235.275537245 861189.66951206
#Sta/Elev= 30
9799.011304.8014 9817.46298.34399847.974285.45719868.267276.02139888.488269.2621
9898.599267.1639 9908.71266.1181 9918.82264.39949928.889261.47639938.949259.0493
 9949.01 257.126 9959.07252.9915 9969.13249.93579979.191248.88589989.251246.6793
10019.41247.455310029.46250.118510039.51253.661710059.61262.361210069.66264.6616
10088.39264.909910099.82265.460610109.91266.9977   10120270.358410130.09271.8968
10150.27273.834910160.36276.576210170.45 281.35310190.63283.778610200.99285.5565
#Mann= 3 , 0 , 0
9799.011    0.12       09799.011    0.12       010200.99    0.12       0
#XS Ineff= 2 , 0
       0                               0
Bank Sta=9799.011,10200.99
Exp/Cntr=0.3,0.1

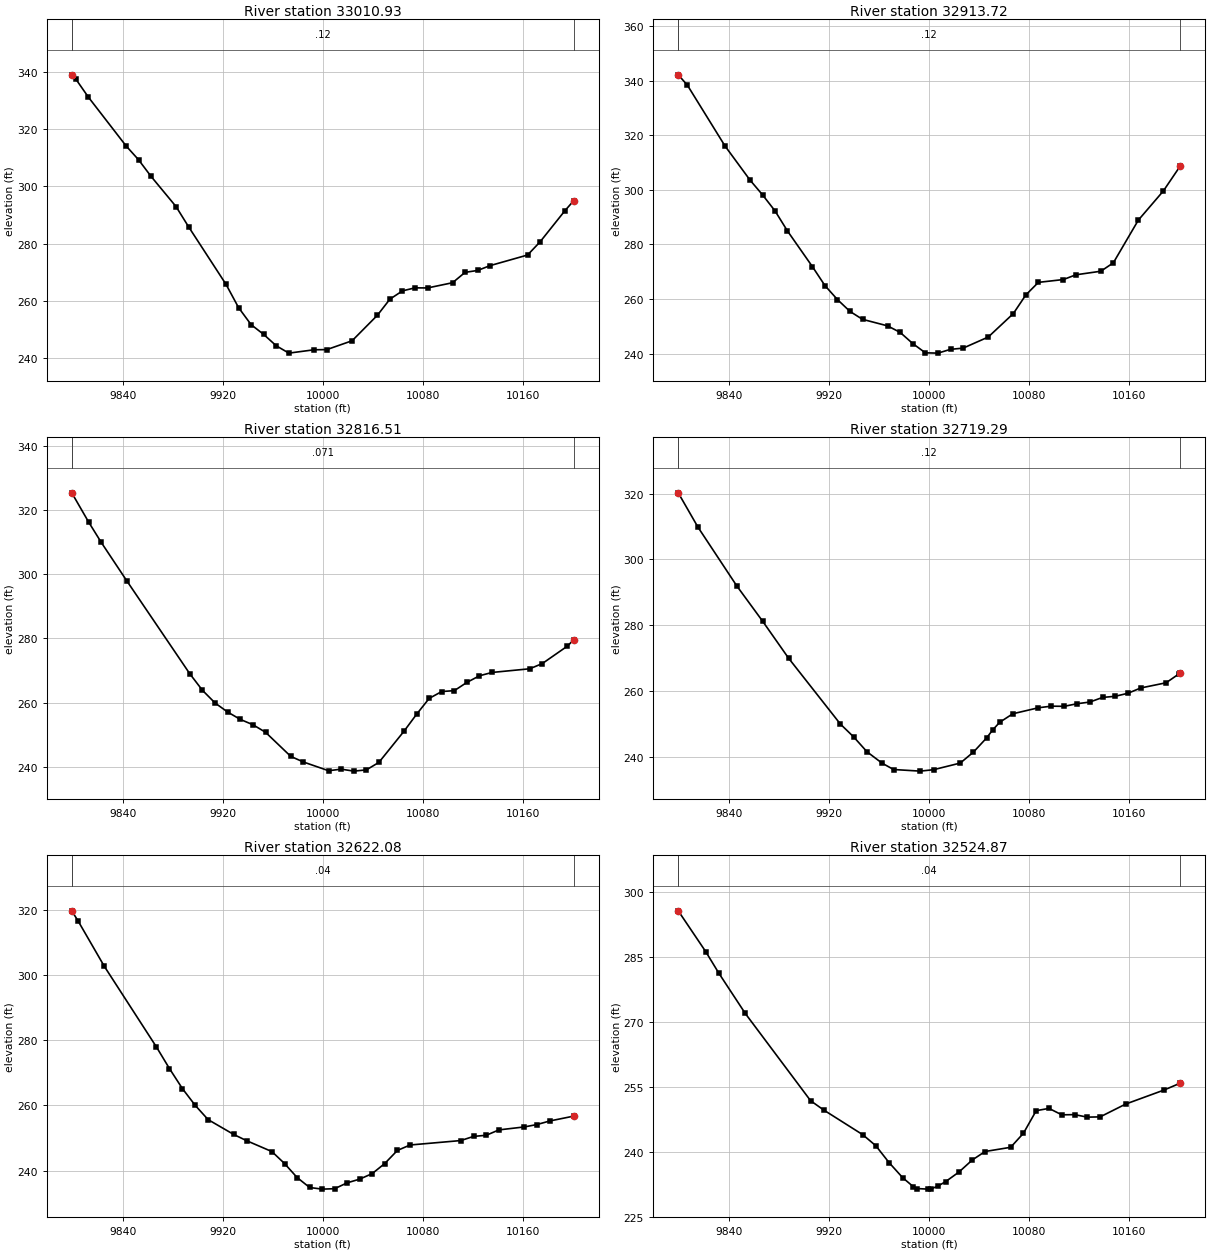
Type RM Length L Ch R = 1 ,33010.93,97.211900,97.211900,97.211900
XS GIS Cut Line= 6
699841.691637296861268.833572241699901.604298855861273.273152317
699954.626454583861273.013777618700121.091107839 861252.44715796
700181.983516188861250.731539172700242.013136977861253.276739822
#Sta/Elev= 30
9799.045339.01669802.362337.4835 9812.39331.18929842.472314.20289852.499309.3414
9862.518 303.5239882.518 292.9779892.518285.94249922.554265.78199932.589257.6544
9942.623251.71189952.658248.30839962.727244.33619972.843241.76619993.075242.9402
 10003.2242.996710023.47246.091410043.67254.987110053.72260.628710063.78263.5221
10073.84264.582810083.87264.541810103.88266.371510113.89269.992810123.89270.6499
10133.89272.342610163.92 276.05310173.93 280.65110193.94291.601810200.96295.0891
#Mann= 3 , 0 , 0
9799.045    0.12       09799.045    0.12       010200.96    0.12       0
#XS Ineff= 2 , 0
       0                               0
Bank Sta=9799.045,10200.96
Exp/Cntr=0.3,0.1

Type RM Length L Ch R = 1 ,32913.72,97.211900,97.211900,97.211900
XS GIS Cut Line= 6
699857.744302124861360.767816636699917.616193085861365.764124463
699970.637112514 861366.42844624700016.891974584861363.675585273
700145.422838944861349.897005296700258.589283848861350.137524331
#Sta/Elev= 30
9799.036342.20169806.317338.43469836.422316.14879856.491303.61619866.501  298.21
9876.501292.32259886.502284.93399906.504271.83629916.512264.9051 9926.53259.7801
9936.547255.44099946.565252.54679966.644250.14989976.716247.75069986.788243.6654
 9996.86240.265810006.94240.156210017.02241.5469 10027.1241.985610047.22246.0596
10067.28254.646810077.32261.495110087.35 266.10210107.36 267.13410117.36268.8752
10137.37270.190310147.37273.269410167.38288.927810187.39299.610210200.98308.8088
#Mann= 3 , 0 , 0
9799.036    0.12       09799.036    0.12       010200.98    0.12       0
#XS Ineff= 2 , 0
       0                               0
Bank Sta=9799.036,10200.98
Exp/Cntr=0.3,0.1

Type RM Length L Ch R = 1 ,32816.51,97.211800,97.211800,97.211800
XS GIS Cut Line= 6
699861.662810833861425.662647842699944.942056201861439.188585541
700059.420076338861455.432165462 700061.40045686861455.711616686
700066.825821406861456.457213956 700260.06527705861478.750971401
#Sta/Elev= 30
9799.005325.48019812.517316.34639822.648309.9747 9842.91298.08569893.534268.9576
9903.634263.81549913.734259.85449923.834257.02169933.935254.72749944.035253.0669
9954.135250.71479974.335243.17869984.435241.429110004.63   238.7 10014.7239.1914
10024.77 238.57410034.84238.9515 10044.9241.299110065.04251.0466 10075.1256.3375
10085.17261.281410095.24 263.434 10105.3263.704510115.37 266.28210125.43268.3499
 10135.5269.3889 10165.7270.535810175.77272.1698 10195.9277.6313   10201 279.636
#Mann= 3 , 0 , 0
9799.005   0.071       09799.005   0.071       0   10201   0.071       0
#XS Ineff= 2 , 0
       0                               0
Bank Sta=9799.005,10201
Exp/Cntr=0.3,0.1

Type RM Length L Ch R = 1 ,32719.29,97.211900,97.211900,97.211900
XS GIS Cut Line= 6
699839.684053975861489.718012878699963.479489233861522.986363636
700058.581784572861558.301414412 700094.26556929 861569.60875656
700151.461168311861583.335062861700226.170186398861597.534460027
#Sta/Elev= 30
 9799.04320.21139814.899309.74059845.964291.90849866.674281.17799887.383269.9809
9928.847249.97379939.496246.06199950.145241.55789962.181238.10429971.442236.1668
 9992.74235.676510003.43236.110310024.84 238.12810035.41241.4765 10045.9245.7559
10050.85248.223910056.39250.508610066.87253.097810087.43 254.92610097.72255.4085
   10108255.357610118.29256.147910128.53256.657910138.71258.060210148.89258.4132
10159.07259.328110169.25260.930610189.61 262.51310199.79265.190110200.98265.3475
#Mann= 3 , 0 , 0
 9799.04    0.12       0 9799.04    0.12       010200.98    0.12       0
#XS Ineff= 2 , 0
       0                               0
Bank Sta=9799.04,10200.98
Exp/Cntr=0.3,0.1

Type RM Length L Ch R = 1 ,32622.08,97.211800,97.211800,97.211800
XS GIS Cut Line= 6
  699810.0127544861597.866439902699891.836143652861622.166333787
699951.384591652861636.032006314699983.940016219861640.388184583
700059.815038203861644.621997101700204.022703893 861670.60193358
#Sta/Elev= 30
9799.049319.67249804.252316.46499825.115 302.6479866.842277.91699877.273271.2879
9887.653265.13929897.921     2609908.188255.65069928.723251.09629938.991249.1946
9959.283245.84639969.372242.18559979.452237.89219989.458 234.8419999.464234.3372
10009.47234.465610019.47 236.26410029.51237.399510039.56239.1008 10049.6 242.189
10059.71246.201710069.87247.868610110.51249.231810120.68250.506310130.84 250.849
   10141252.502610161.32253.406310171.48254.145710181.64255.229710200.97256.7335
#Mann= 3 , 0 , 0
9799.049    0.04       09799.049    0.04       010200.97    0.04       0
#XS Ineff= 2 , 0
       0                               0
Bank Sta=9799.049,10200.97
Exp/Cntr=0.3,0.1

Type RM Length L Ch R = 1 ,32524.87,97.211900,97.211900,97.211900
XS GIS Cut Line= 6
699794.146410521861666.284974571 699950.33461823861715.237029024
699971.995553112861724.465242367699995.768611911 861738.47274789
 700014.95846239  861745.6479389700177.706550789 861781.05413603
#Sta/Elev= 30
9799.044 295.632 9821.06286.20929831.618281.20249852.732271.93129905.007251.7891
9915.442249.65719946.748243.94889957.183241.40699967.821237.50469978.691234.0266
9987.347231.91389989.783231.5225    9999231.382810001.51231.439110006.87232.0805
10013.01233.101310023.75 235.32710034.43238.112810044.66240.068510065.13241.0399
10075.36244.2775 10085.6249.496610095.83250.021110106.07248.5347 10116.3 248.583
10126.53248.000910136.77248.063410157.24251.024810187.94 254.26210200.94 255.855
#Mann= 3 , 0 , 0
9799.044    0.04       09799.044    0.04       010200.94    0.04       0
#XS Ineff= 2 , 0
       0                               0
Bank Sta=9799.044,10200.94
Exp/Cntr=0.3,0.1