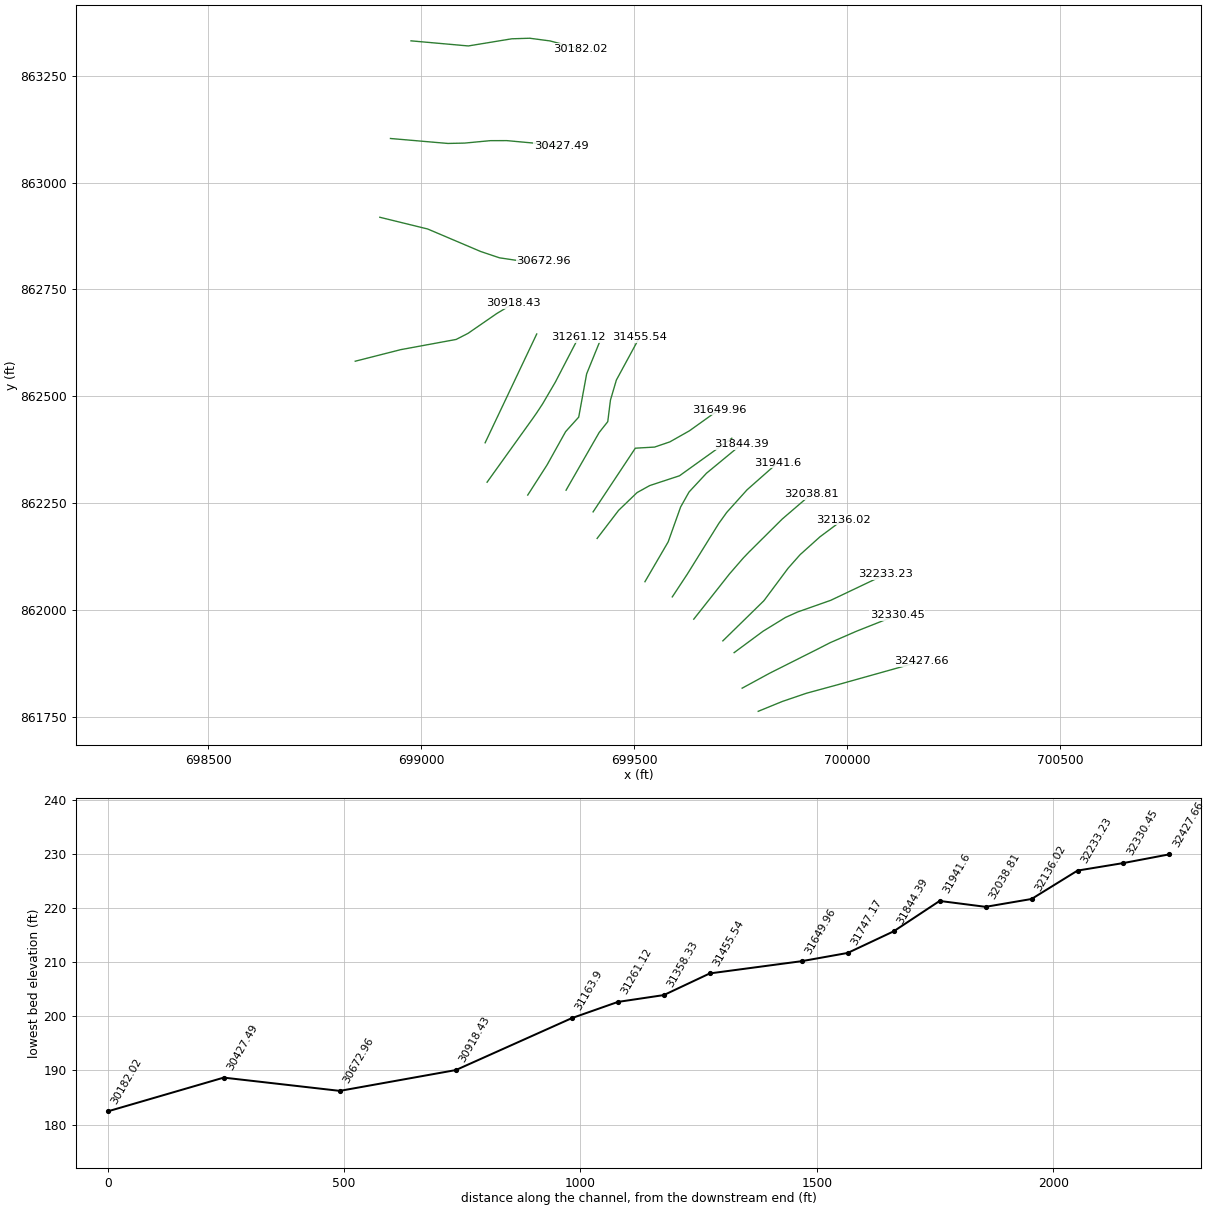
HEC-RAS study 13600_ras.prj: 13600

--- 13600_ras.g01 (geometry) --- (continued)

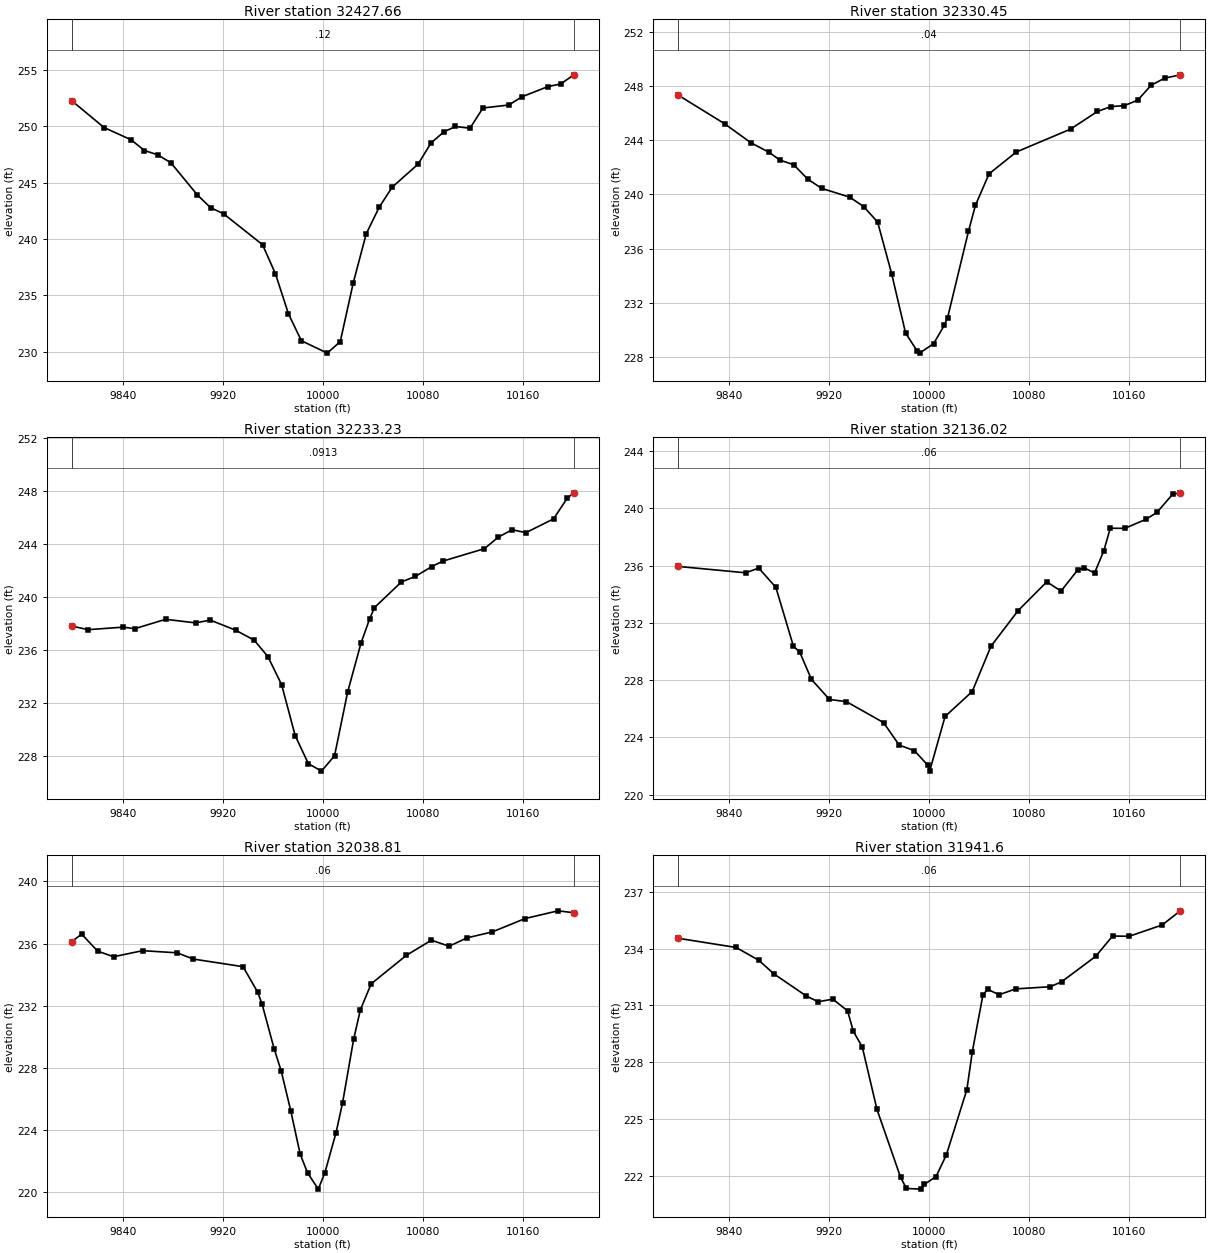
Type RM Length L Ch R = 1 ,32427.66,97.211900,97.211900,97.211900
XS GIS Cut Line= 6
699790.998238004861763.140722917699847.536920608861786.169232466
699904.316963171861805.454165174699980.524910132861826.114715242
 699982.43455621861826.709065189700175.072374894861880.458454529
#Sta/Elev= 30
9799.027252.25769824.943249.87419846.538248.79239857.336247.83619867.957247.4556
9878.518246.7444 9899.64243.90419910.201242.78039920.749242.22119951.832 239.493
9962.193236.90699972.554233.36999982.915230.984410003.66 229.88710014.05230.9129
10024.43236.113810034.81240.454910045.19 242.81110055.57244.588510076.34246.6324
10086.72248.5116 10097.1249.499610106.27249.965910117.86249.811810128.25251.6066
10149.01251.869510159.39252.595110180.16253.498210190.54253.7376   10201254.5436
#Mann= 3 , 0 , 0
9799.027    0.12       09799.027    0.12       0   10201    0.12       0
#XS Ineff= 2 , 0
       0                               0
Bank Sta=9799.027,10201
Exp/Cntr=0.3,0.1

Type RM Length L Ch R = 1 ,32330.45,97.211800,97.211800,97.211800
XS GIS Cut Line= 6
699753.316500297861817.279662932699817.313514712 861851.98812396
699931.005775976861908.979907964699959.902114929861923.719679975
700021.929946515861950.616735261700116.735046295861988.068408992
#Sta/Elev= 30
 9799.02247.34429836.189245.22679857.165243.82789871.823243.11379880.421242.5453
9891.607 242.1939902.793241.13139913.979240.44869936.352239.80219947.538239.1065
9958.724237.9602 9969.91234.15019981.096229.75999990.119228.47229992.282228.2787
10003.53228.977310012.14230.345110014.74  230.9110031.44237.2835   10037239.2011
 10047.9241.5232 10069.7243.1372 10113.1244.826210134.61246.131110145.36246.4913
10156.11246.562110166.86246.965210177.61248.066610188.37248.589310200.98248.8388
#Mann= 3 , 0 , 0
 9799.02    0.04       0 9799.02    0.04       010200.98    0.04       0
#XS Ineff= 2 , 0
       0                               0
Bank Sta=9799.02,10200.98
Exp/Cntr=0.3,0.1

Type RM Length L Ch R = 1 ,32233.23,97.211900,97.211900,97.211900
XS GIS Cut Line= 6
699734.456790378861900.393135193699802.348936585861950.470201165
699854.911410179  861982.6825815699883.227235723861995.416106768
699961.282586111862022.838242146700089.672986777862083.650433631
#Sta/Elev= 30
9799.075237.82759812.176237.5497 9840.53237.74159849.454237.62059874.306238.3319
9898.276238.06179910.004 238.2719930.383237.50899945.183236.75679956.148235.5165
9967.112233.40199977.997229.55689988.512227.44779999.026226.884710009.48228.0449
10019.96232.852710030.67236.544510037.54238.357810041.41239.215910063.03241.1517
10074.09241.562710087.33242.308910096.22242.720910129.42243.657810140.48 244.524
10151.55245.083710162.61244.864910184.74245.902310195.81247.479610200.98247.8675
#Mann= 3 , 0 , 0
9799.075  0.0913       09799.075  0.0913       010200.98  0.0913       0
#XS Ineff= 2 , 0
       0                               0
Bank Sta=9799.075,10200.98
Exp/Cntr=0.3,0.1

Type RM Length L Ch R = 1 ,32136.02,97.211800,97.211800,97.211800
XS GIS Cut Line= 6
699708.006977375861927.930994162699804.424918636862021.963144485
699861.209924893862097.969406074699889.387953696862129.675512609
699935.755178163862171.201111021699989.988006867862211.536450032
#Sta/Elev= 30
9799.027235.94969853.163235.50429863.509235.83449877.231234.49379891.333230.3624
9896.306229.97319905.747228.04819920.161226.65189933.746226.49779963.473225.0317
9975.948223.46139988.144223.0734    9999222.035910000.33221.642310012.66225.4624
10034.38 227.20510049.43230.376110071.09232.856310094.06234.870410105.47234.2273
 10118.9235.715910124.04235.846410132.32235.4933 10139.7 237.04410144.86238.6199
10156.46238.610210173.21239.233110182.24239.723510194.71240.991210200.92241.0938
#Mann= 3 , 0 , 0
9799.027    0.06       09799.027    0.06       010200.92    0.06       0
#XS Ineff= 2 , 0
       0                               0
Bank Sta=9799.027,10200.92
Exp/Cntr=0.3,0.1

Type RM Length L Ch R = 1 ,32038.81,97.211900,97.211900,97.211900
XS GIS Cut Line= 6
699639.763601171861978.722693947699723.383863732 862084.35836672
699755.969241104862121.795122894699768.167094892862134.516735663
699847.298660903862212.905355166699914.611465312862270.482230695
#Sta/Elev= 30
9799.017236.11949807.023236.60219819.777235.51399832.531235.14789855.789235.5393
9883.546235.3998  9896.3235.00069936.205234.50879947.852232.87479951.436232.1014
9961.109229.21919966.668227.81839974.367225.24379981.899222.45349987.817221.2434
9996.418220.193910001.69221.249210010.62223.8242 10015.9225.763810024.69229.8265
10030.11 231.73510038.77233.407510066.92235.238910086.94236.212310101.15235.8265
10115.61236.367110135.68236.7461   10162237.608310188.32238.103110200.96237.9806
#Mann= 3 , 0 , 0
9799.017    0.06       09799.017    0.06       010200.96    0.06       0
#XS Ineff= 2 , 0
       0                               0
Bank Sta=9799.017,10200.96
Exp/Cntr=0.3,0.1

Type RM Length L Ch R = 1 , 31941.6,97.211900,97.211900,97.211900
XS GIS Cut Line= 6
699589.359148947862030.843128432699624.479934792862083.900225482
699698.687229114862202.946928647699717.172031993862228.530788251
699764.844110504862281.370813947699836.349972325862344.299014475
#Sta/Elev= 30
 9799.01234.54269845.463234.05619863.622 233.3779875.715232.65869901.448231.4978
9911.059 231.1869922.841231.32439934.622 230.7099939.275229.62079946.404228.7969
9958.185225.49319977.102221.90259981.748 221.3179993.529221.28179996.016 221.528
10005.45221.9441 10013.7223.090710030.13226.541210034.48228.541510042.93231.5319
10046.66231.846210055.98231.5574 10069.2231.866810096.87231.9808 10105.9232.2405
10133.16233.582510146.79 234.66210160.07234.647210186.49235.246610200.97235.9933
#Mann= 3 , 0 , 0
 9799.01    0.06       0 9799.01    0.06       010200.97    0.06       0
#XS Ineff= 2 , 0
       0                               0
Bank Sta=9799.01,10200.97
Exp/Cntr=0.3,0.1

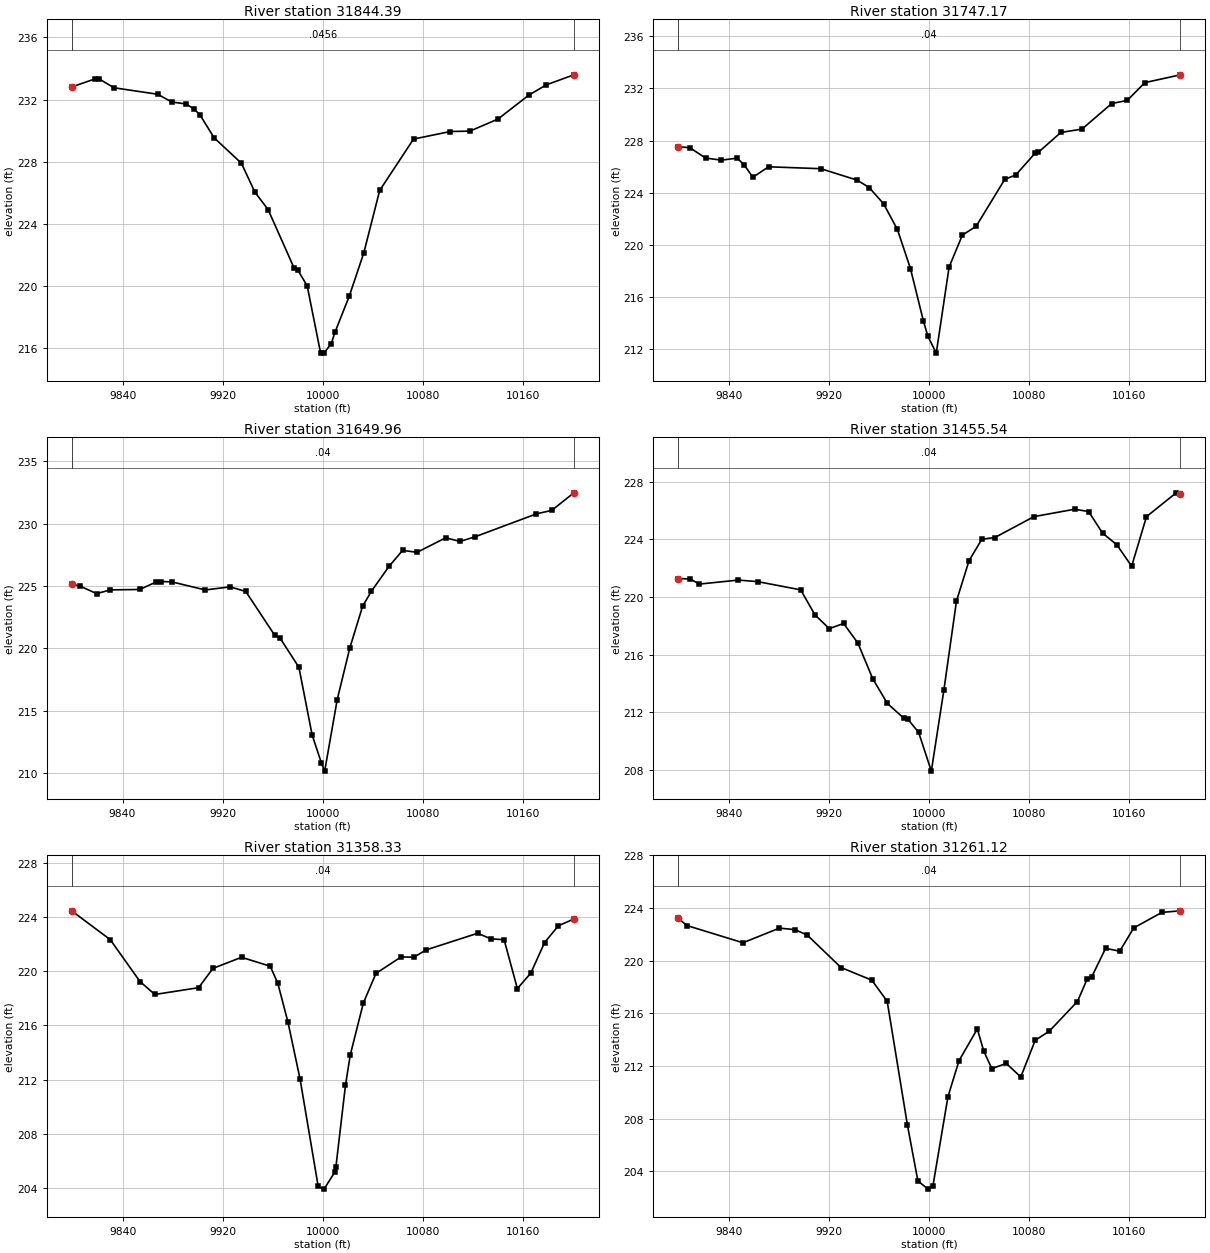
Type RM Length L Ch R = 1 ,31844.39,97.211800,97.211800,97.211800
XS GIS Cut Line= 6
699525.156439167862066.296934432 699579.68672069862159.536947843
699608.931051599862241.198631212699628.714027668862276.306134287
699669.496612155862320.027295619699751.902456706862387.822767304
#Sta/Elev= 30
9799.069232.80719817.717233.32679821.089 233.3269832.863232.75769867.885232.3396
9879.249231.83789890.613231.71679897.268231.37589901.977230.98129913.084229.5345
 9934.87227.90239945.749226.03069956.252 224.9189977.121221.14339980.259 220.995
9987.556     220 9998.25215.6962   10001215.673110006.84216.290810009.75  217.01
10021.29219.355910032.83222.121410045.56226.145110072.65 229.45310102.05229.9398
10117.79229.966510140.19230.739810165.01232.289510179.04232.948310200.93233.5895
#Mann= 3 , 0 , 0
9799.069  0.0456       09799.069  0.0456       010200.93  0.0456       0
#XS Ineff= 2 , 0
       0                               0
Bank Sta=9799.069,10200.93
Exp/Cntr=0.3,0.1

Type RM Length L Ch R = 1 ,31747.17,97.211900,97.211900,97.211900
XS GIS Cut Line= 6
699412.922225203862167.561107875699463.426789555862233.340177986
699506.707226123862274.845990706699536.440542518862291.280349919
699606.258601435 862314.16245899699729.034510542862401.927211259
#Sta/Elev= 30
9799.118 227.5269808.497227.45319821.104226.65869833.712226.49749846.319226.6512
9851.791226.15819858.927225.18599871.534 225.9889913.345225.84039942.403224.9619
 9951.97224.39699963.509223.14659974.569221.17499985.025218.16719995.381214.1452
    9999212.964810005.66211.682810015.94218.294610026.54220.742110037.55221.4216
10060.47225.018310069.41225.374910084.54227.011410087.38227.105310105.34228.6213
10122.26228.883610146.03 230.842 10158.5231.086710172.54232.447910200.91233.0475
#Mann= 3 , 0 , 0
9799.118    0.04       09799.118    0.04       010200.91    0.04       0
#XS Ineff= 2 , 0
       09809.617                       0
Bank Sta=9799.118,10200.91
Exp/Cntr=0.3,0.1

Type RM Length L Ch R = 1 ,31649.96,194.423700,194.423700,194.423700
XS GIS Cut Line= 6
699403.467676531862229.694292854699502.570727492862378.677293353
699547.777256297862381.311207271699583.531248274862393.398460351
699629.251978185862419.149602687699699.369516521862469.109205991
#Sta/Elev= 30
9799.301225.12969805.807225.00129819.229224.3923 9830.33224.68949853.789 224.723
9867.116225.33539871.069225.35759879.378225.33419906.124224.68369925.996 224.932
9938.529224.56259961.673221.05439965.739220.85969981.033218.48579991.571213.0783
    9999210.820610001.63210.164310011.68215.904610021.71220.027710031.96223.3789
10038.92224.5665 10053.1226.5766   10064227.858710075.48 227.69710098.43228.8658
10109.91228.573610121.84 228.94310170.96230.782510183.24231.062910200.88232.4683
#Mann= 3 , 0 , 0
9799.301    0.04       09799.301    0.04       010200.88    0.04       0
#XS Ineff= 2 , 0
       0                               0
Bank Sta=9799.301,10200.88
Exp/Cntr=0.3,0.1

Type RM Length L Ch R = 1 ,31455.54,97.211900,97.211900,97.211900
XS GIS Cut Line= 6
 699340.04632654 862280.50755819699417.733716113862415.404275803
699437.906059997862440.831109534699444.188081277862491.078433901
699458.098123732862538.117689476699512.332666574862637.778842509
#Sta/Elev= 30
9799.222221.27549808.796221.25049816.158220.8931 9847.45221.1705  9862.9221.0629
9897.232220.49289908.676218.7539 9920.12217.79839931.564218.15749943.008216.7949
9954.914214.30699966.606 212.6039979.928211.56149982.695211.53829991.605210.5865
10001.72207.903210011.79213.547410021.85219.720310031.92222.526810042.13224.0069
10052.56224.127710083.84225.578810116.31226.091810127.52225.929210138.72224.4282
10150.13223.617710161.93222.1314 10173.8225.576410197.54227.230210200.84227.1752
#Mann= 3 , 0 , 0
9799.222    0.04       09799.222    0.04       010200.84    0.04       0
#XS Ineff= 2 , 0
       0                               0
Bank Sta=9799.222,10200.84
Exp/Cntr=0.3,0.1

Type RM Length L Ch R = 1 ,31358.33,97.211800,97.211800,97.211800
XS GIS Cut Line= 6
699250.070893378862269.033785831699295.597257079862339.762500659
699338.970954395862417.406107807699369.704103634862451.325623712
699388.340691494862552.604515021699418.308274753862626.135557189
#Sta/Elev= 30
9799.068224.46489829.949222.33569853.734219.24369865.626218.28519900.636218.7858
9912.091220.2126    9935221.03119957.909220.37349963.977 219.122 9972.12216.2463
9981.842212.02289996.315204.1083   10001203.905310009.83205.198810010.48205.5352
10018.15211.5913   10022213.826810032.45217.654910042.53219.840310062.69221.0621
10072.77221.037410082.85221.582510123.88222.806810134.47222.397410145.07222.3288
10155.67218.719910166.38219.859110177.45222.122510188.52223.363210200.85223.8604
#Mann= 3 , 0 , 0
9799.068    0.04       09799.068    0.04       010200.85    0.04       0
#XS Ineff= 2 , 0
       09858.845                       0
Bank Sta=9799.068,10200.85
Exp/Cntr=0.3,0.1

Type RM Length L Ch R = 1 ,31261.12,97.211900,97.211900,97.211900
XS GIS Cut Line= 6
699154.671353527862299.166123298699261.864962829862448.156701923
699271.306128911 862461.62449978699284.987787025862482.395612538
699314.792355365862533.129163582699369.356751147862638.041170739
#Sta/Elev= 30
9799.008223.22529806.195222.66939850.939221.3643 9880.11222.47789892.429222.3616
9902.307221.95489929.387219.48329954.025218.52249966.345216.92089982.553207.5053
 9990.91203.2682    9999202.640210003.01202.9108   10015209.668710023.87212.4069
10038.49214.812110043.64213.132310050.09211.801810061.69212.191910073.29211.1652
10084.82213.949310096.09214.643610118.64216.900110126.51218.624510129.91  218.74
10141.18220.943110152.45220.721210163.72222.492910186.27 223.67410200.97223.7914
#Mann= 3 , 0 , 0
9799.008    0.04       09799.008    0.04       010200.97    0.04       0
#XS Ineff= 2 , 0
       09907.165                       0
Bank Sta=9799.008,10200.97
Exp/Cntr=0.3,0.1

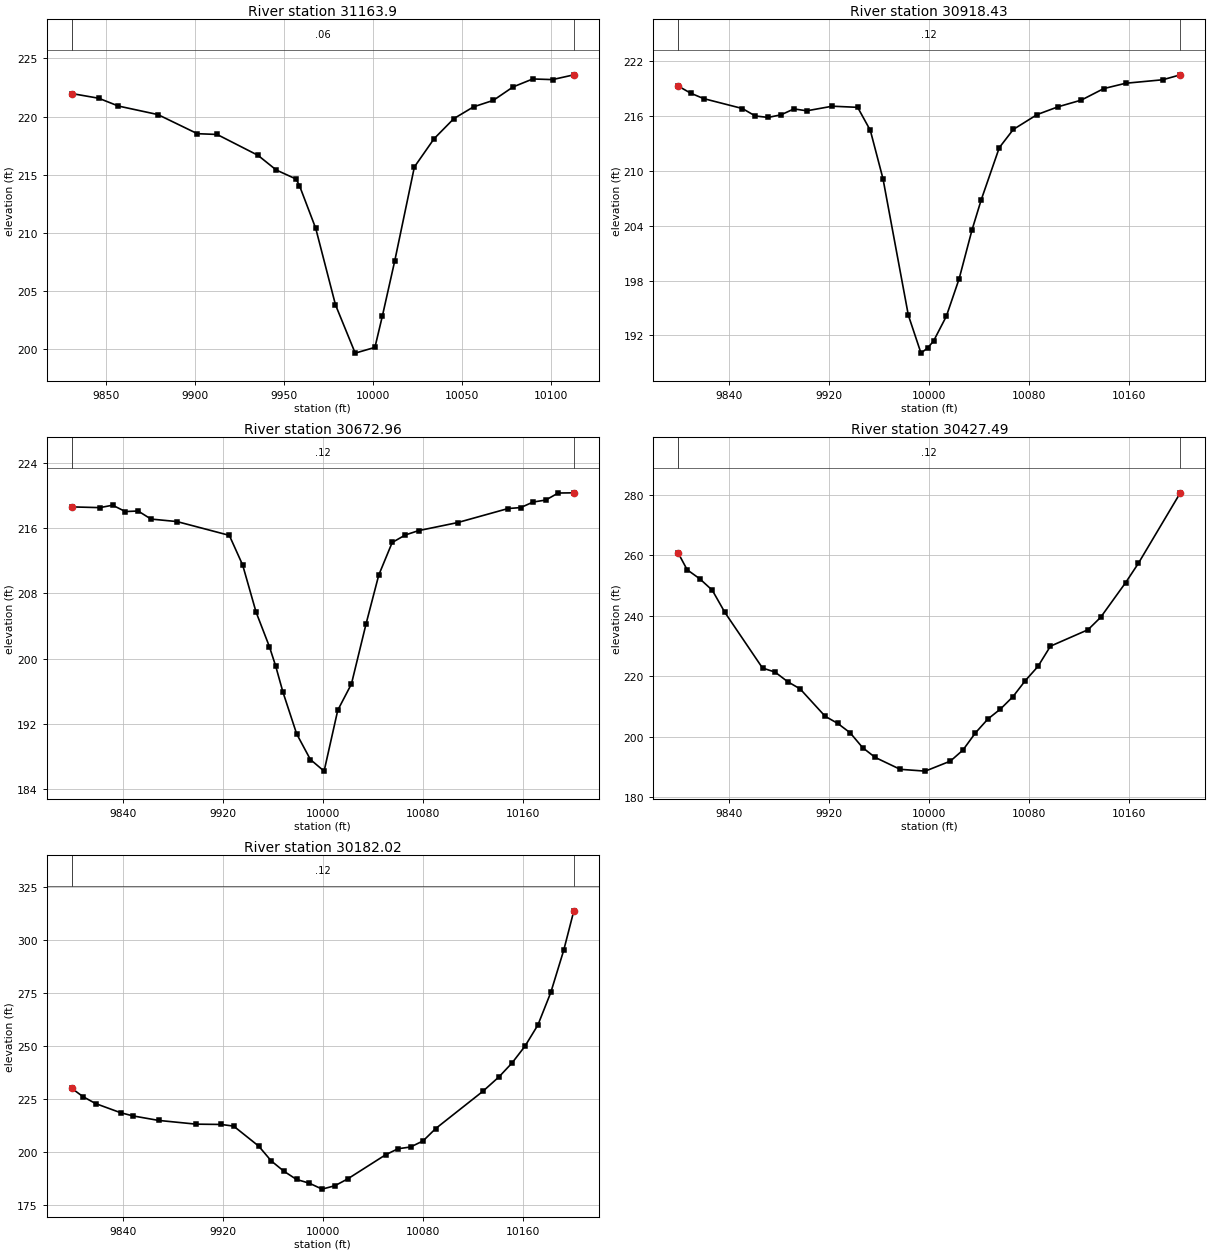
Type RM Length L Ch R = 1 , 31163.9,245.470300,245.470300,245.470300
XS GIS Cut Line= 2
699150.108665824862391.347116441699271.169029057 862645.82094124
#Sta/Elev= 25
9830.881221.9805    9846221.57659857.074220.90459879.222220.17249901.369218.5274
9912.443218.46239935.378216.66919945.665 215.4039956.739214.63189958.656214.0711
9967.813210.38329978.887203.81359989.961199.655410001.03200.149310005.21202.8448
10012.11207.556110023.18215.668210034.26218.100310045.33 219.824 10056.4220.8386
10067.48221.393410078.55222.548110089.63223.2347 10100.7223.179910112.68223.5905
#Mann= 3 , 0 , 0
9830.881    0.06       09830.881    0.06       010112.68    0.06       0
#XS Ineff= 2 , 0
       09870.662                       0
Bank Sta=9830.881,10112.68
Exp/Cntr=0.3,0.1

Type RM Length L Ch R = 1 ,30918.43,245.470200,245.470200,245.470200
XS GIS Cut Line= 6
698845.239499553862582.170961677698952.099940539862609.234443742
699082.072646643862633.090137984699109.868335085862647.266614024
699177.515328469862693.780081601 699217.06517918862717.454603663
#Sta/Elev= 30
9799.042219.26089809.111218.48149819.427217.89369850.374216.81189860.689215.9962
9871.005215.83869881.321216.12359891.637216.76639901.952216.56199922.357217.0634
9942.637216.94089952.777214.42299962.918209.13159983.198194.21749993.338190.0615
    9999190.669610003.47191.4056 10013.6194.083810023.87198.192210034.19203.5436
 10041.5206.810210056.01212.533710067.23214.523610086.35216.1529 10103.2217.0067
10121.65217.731910139.61218.990310157.17219.574610186.83219.955210200.89220.4956
#Mann= 3 , 0 , 0
9799.042    0.12       09799.042    0.12       010200.89    0.12       0
#XS Ineff= 2 , 0
       09818.932                       0
Bank Sta=9799.042,10200.89
Exp/Cntr=0.3,0.1

Type RM Length L Ch R = 1 ,30672.96,245.470300,245.470300,245.470300
XS GIS Cut Line= 6
698902.971856022862918.920099683699015.337111555862891.462257869
699139.822690408862838.754742366699183.915853007862824.017880026
699241.516476693862815.482636438699287.522778566862817.581181407
#Sta/Elev= 30
9799.042218.61559821.528218.52549831.735218.82249841.943218.0431 9852.15218.1106
9862.451217.12379883.249216.81599925.137215.12639935.837211.48149946.538205.7242
9957.239201.47219962.196199.12979968.082195.8974 9979.05190.78289990.017 187.645
   10001186.220810011.94193.692710022.88196.908110034.63204.301210044.75210.2601
10055.49214.250110066.03215.175310076.58215.703610107.82216.6908 10148.3218.4158
10158.32  218.5310168.33 219.21410178.35219.450810188.36220.315710200.89220.3398
#Mann= 3 , 0 , 0
9799.042    0.12       09799.042    0.12       010200.89    0.12       0
#XS Ineff= 2 , 0
       0                               0
Bank Sta=9799.042,10200.89
Exp/Cntr=0.3,0.1

Type RM Length L Ch R = 1 ,30427.49,245.470200,245.470200,245.470200
XS GIS Cut Line= 6
698927.911992629 863103.19205966699062.633236411863091.601492727
699102.172892494863092.454197157699162.543095266 863098.14165392
 699200.83441096863098.222013641699328.475608769863086.530399576
#Sta/Elev= 30
9799.031260.78729806.161 255.2839816.219252.29979826.277 248.5159836.336241.1844
9866.511222.76329876.566221.42819886.582218.26729896.598215.87049916.631206.8113
9926.647204.4737 9936.66201.34289946.663196.42969956.665193.21229976.682189.2686
9996.776188.668110016.87191.977510026.91 195.61610036.94201.313410046.94205.9122
10056.94209.186310066.94213.281510076.95218.632910086.97223.277910096.99229.9946
10127.09235.440810137.15239.521410157.26251.053910167.31257.347810200.97280.7229
#Mann= 3 , 0 , 0
9799.031    0.12       09799.031    0.12       010200.97    0.12       0
#XS Ineff= 2 , 0
       0                               0
Bank Sta=9799.031,10200.97
Exp/Cntr=0.3,0.1

Type RM Length L Ch R = 1 ,30182.02,245.470300,245.470300,245.470300
XS GIS Cut Line= 6
698976.088290026863331.642890267699110.571256112 863319.69907115
699212.648934184863336.411963593699254.706547745863337.733051745
699302.466909926863331.422004311699372.830753446863312.837019828
#Sta/Elev= 30
9799.077229.94029808.053226.04299818.126222.7789 9838.27218.43699848.343216.9248
9868.488214.83519898.582213.06749918.601212.9279 9928.61212.14189948.664202.7129
9958.699195.73189968.733190.90839978.915186.9967 9989.15185.23399999.389182.4313
10009.61184.028110019.81187.224510050.17198.609710060.17201.478710070.18202.2914
10080.19205.168210090.27210.983710128.07228.568810141.03235.418710151.37241.9118
10161.71249.805910172.06259.8022 10182.4275.176410192.74295.075210200.84313.6581
#Mann= 3 , 0 , 0
9799.077    0.12       09799.077    0.12       010200.84    0.12       0
#XS Ineff= 2 , 0
       0                               0
Bank Sta=9799.077,10200.84
Exp/Cntr=0.3,0.1