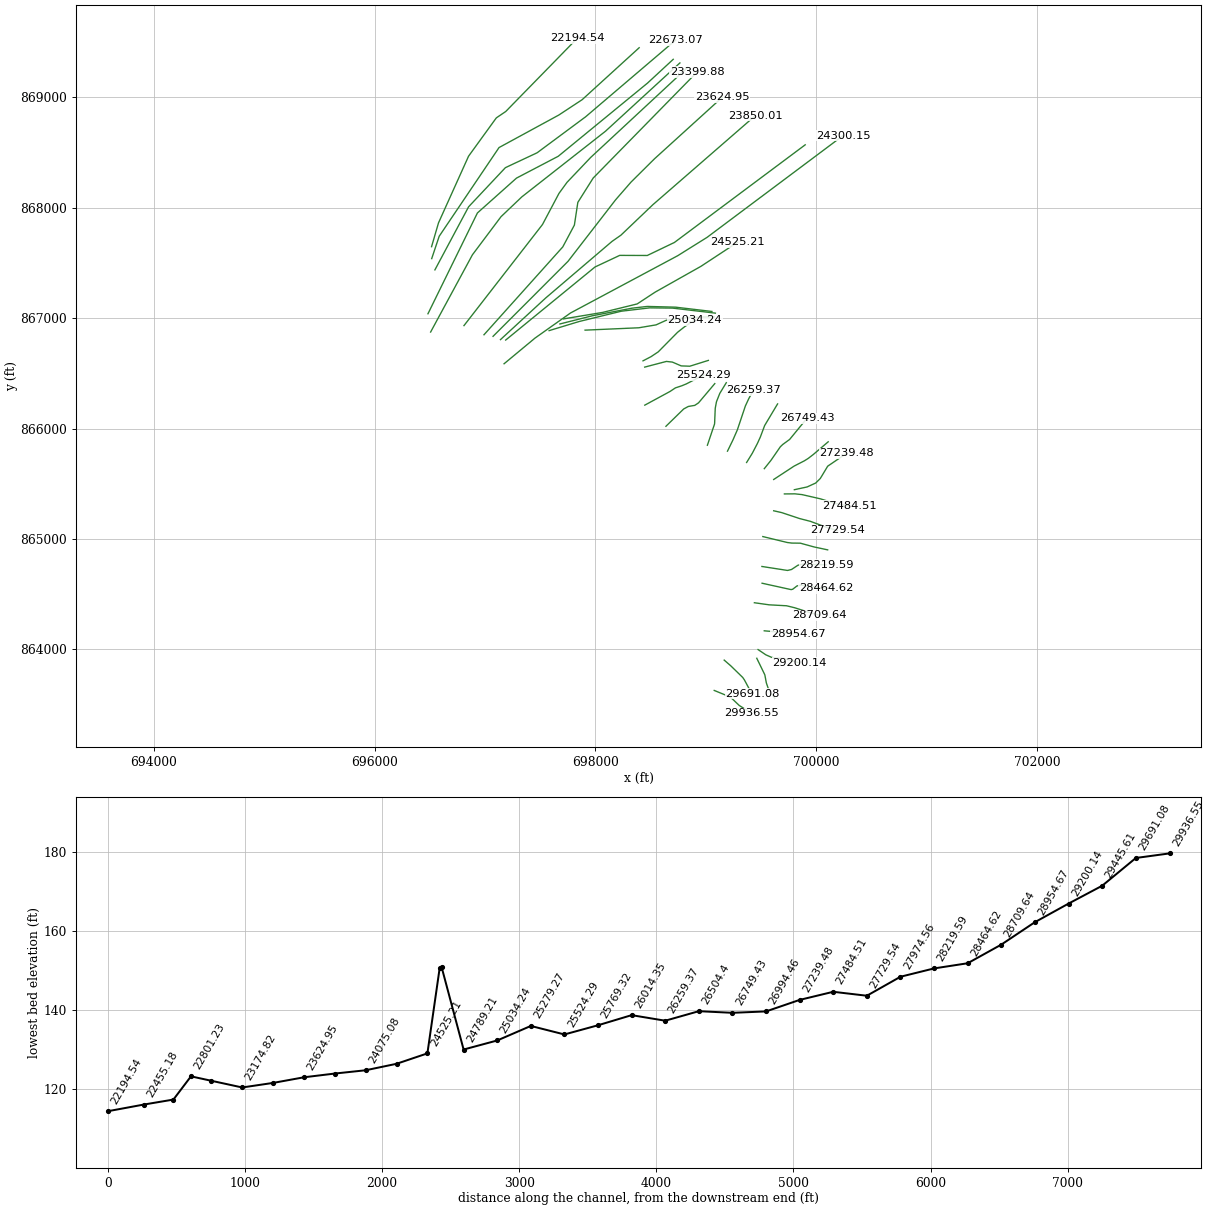
HEC-RAS study 13600_ras.prj: 13600

--- 13600_ras.g01 (geometry) --- (continued)

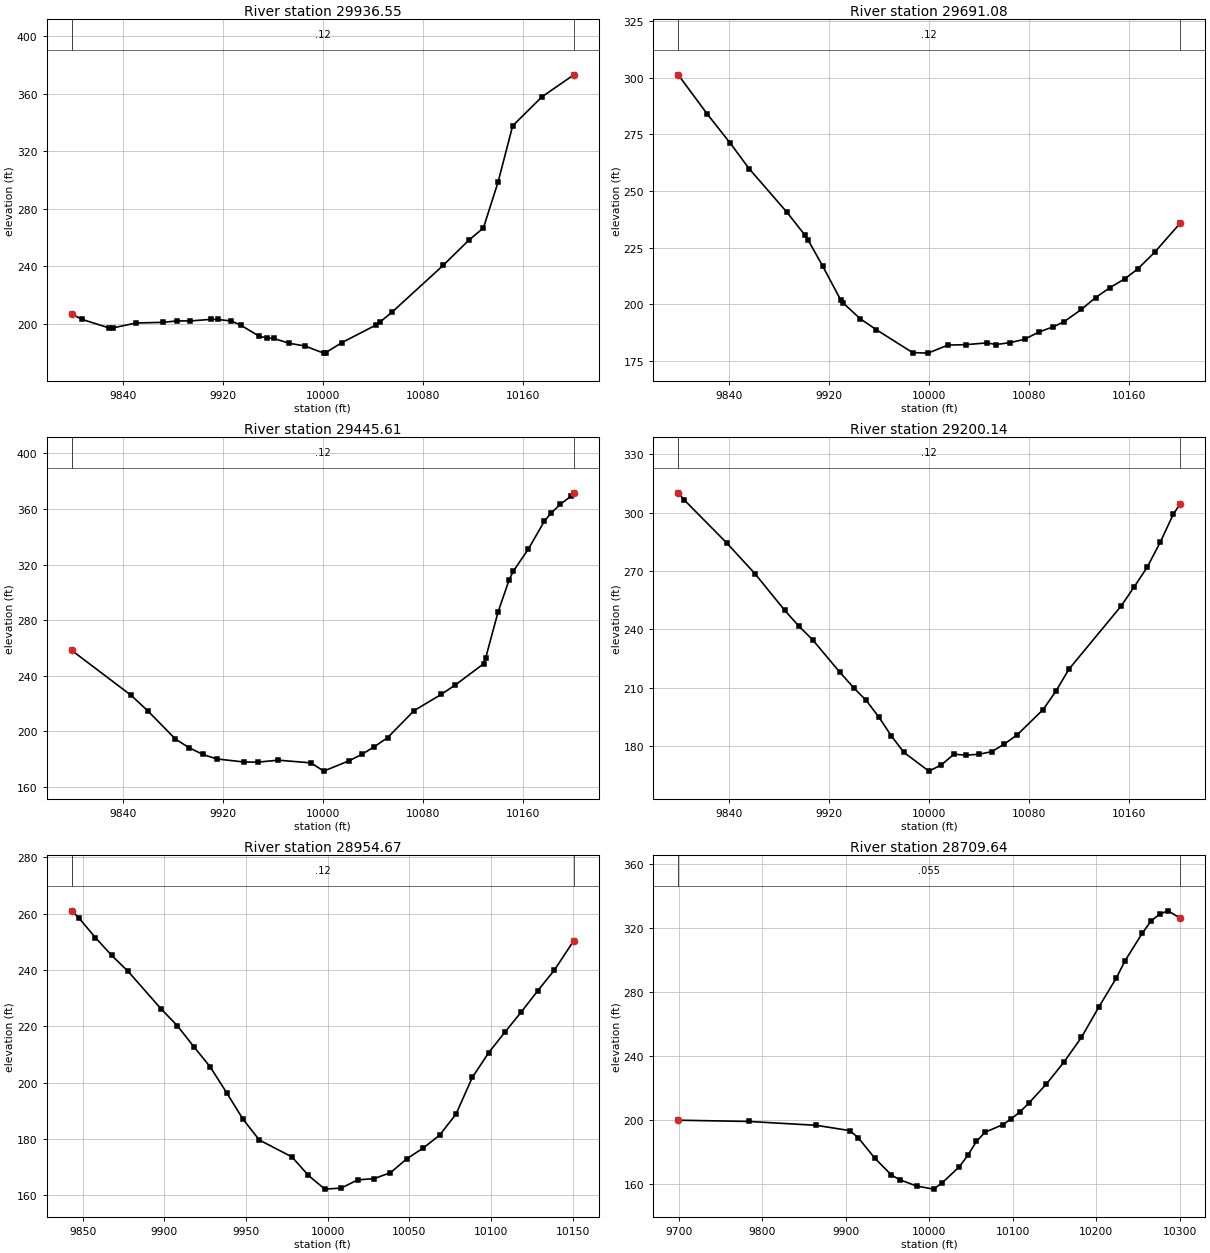
Type RM Length L Ch R = 1 ,29936.55,245.470200,245.470200,245.470200
XS GIS Cut Line= 6
699077.253326836863627.427239939699172.582675316863588.393633109
699226.402866771863561.663105271699243.359528767863548.961089691
699303.123969965863491.908910516699416.796834464863419.636559423
#Sta/Elev= 30
9799.065 206.7129807.436203.07669829.048197.14219831.861197.19449850.659200.6154
9872.271201.05099883.077202.05039893.883202.03279910.212  203.139915.739203.0565
9926.742202.02379934.184199.15949949.226191.35699955.212190.26189960.606189.8641
9973.317186.47099985.807 184.60110000.66179.657810002.29179.9959 10015.4187.0298
10042.65199.239410045.71201.211910055.65208.333410096.29240.631210116.82258.1233
10128.54266.669910140.26298.480310151.97337.683910175.41357.842610200.94373.1382
#Mann= 3 , 0 , 0
9799.065    0.12       09799.065    0.12       010200.94    0.12       0
#XS Ineff= 2 , 0
       0                               0
Bank Sta=9799.065,10200.94
Exp/Cntr=0.3,0.1

Type RM Length L Ch R = 1 ,29691.08,245.470300,245.470300,245.470300
XS GIS Cut Line= 6
699167.472807233 863902.24865417699227.213818301863850.405732768
699335.049470633863745.398476048 699349.99020733863723.841008671
699390.744089344863648.331324512699423.628889841863597.878650444
#Sta/Elev= 30
9799.037301.26779822.243283.99489840.611271.15529855.869259.80999885.891240.7443
9900.239230.70299902.939228.44739914.586216.96649928.933202.10689930.831200.7048
9944.776193.63769957.628188.82359986.613178.7466    9999178.501610014.91182.0525
10029.14182.226110046.12183.015710053.47182.291110064.93183.162410076.29184.6199
10087.66187.795610099.02190.070310107.54192.242710121.75197.784910133.11203.0224
10144.66207.4116 10156.6211.331610166.79215.610610180.47 223.04910200.91235.8891
#Mann= 3 , 0 , 0
9799.037    0.12       09799.037    0.12       010200.91    0.12       0
#XS Ineff= 2 , 0
       0                               0
Bank Sta=9799.037,10200.91
Exp/Cntr=0.3,0.1

Type RM Length L Ch R = 1 ,29445.61,245.470200,245.470200,245.470200
XS GIS Cut Line= 6
699462.750872837863918.920718843699535.537981616 863769.28061764
699549.524447025863695.268167735699564.732958609863651.415449232
699588.296011809 863607.38123661699626.463443516 863556.64899656
#Sta/Elev= 30
9799.081258.25079846.334226.1633  9859.9214.85389881.972194.58539893.008188.2856
9904.044183.45559915.079180.25189937.151178.01469948.187177.95449964.262179.3452
9990.566177.419910000.67171.481110020.95178.911810031.09183.474810041.25189.0536
10051.83195.5604   10073214.974910094.65226.6036   10106233.405910128.68248.6871
10130.33253.016110140.21285.877110149.17309.247410152.34315.105510164.47 331.167
10177.26351.162410182.62357.006310190.12363.389510198.53369.149610200.86371.5857
#Mann= 3 , 0 , 0
9799.081    0.12       09799.081    0.12       010200.86    0.12       0
#XS Ineff= 2 , 0
       0                               0
Bank Sta=9799.081,10200.86
Exp/Cntr=0.3,0.1

Type RM Length L Ch R = 1 ,29200.14,245.470300,245.470300,245.470300
XS GIS Cut Line= 6
699474.448875694863997.717329183699544.306228749863950.522288669
699595.675663725863927.743422757699626.620098231863921.344953836
699708.240896992863917.559880478699850.278656088863877.132721656
#Sta/Elev= 30
9799.122310.23099803.759 306.6689837.884284.45379860.756268.44979884.257249.7861
9895.461241.75049906.665234.58729928.321217.96269939.748209.7369 9949.27203.5657
9959.481194.98379969.693185.07429979.727 176.5979999.729 166.96110009.73170.1707
10019.73175.652410029.79175.188510039.87175.649510049.95176.974310060.19180.9164
 10070.5185.715110091.13198.643710101.44208.192110111.75219.399210153.58251.9539
10164.04261.8107 10174.5  272.0210184.96284.888710195.42299.340410200.94304.5369
#Mann= 3 , 0 , 0
9799.122    0.12       09799.122    0.12       010200.94    0.12       0
#XS Ineff= 2 , 0
       0                               0
Bank Sta=9799.122,10200.94
Exp/Cntr=0.3,0.1

Type RM Length L Ch R = 1 ,28954.67,245.027000,245.027000,245.027000
XS GIS Cut Line= 2
699530.584093183864167.722650632699836.940930754864140.545834392
#Sta/Elev= 30
9843.239261.06679847.672 258.4879857.711251.55159867.751245.2127 9877.79239.5468
9897.868226.30329907.908220.25439917.947212.87749927.986205.69089938.025196.5649
9948.065187.15399958.104179.71029978.183173.66939988.222167.11129998.261162.2595
 10008.3162.629910018.34165.529510028.38165.993310038.42168.075310048.46173.0176
 10058.5176.823910068.54181.409310078.58188.860810088.61201.912810098.65210.7195
10108.69218.078810118.73225.241710128.77232.749910138.81239.9718 10150.8250.4972
#Mann= 3 , 0 , 0
9843.239    0.12       09843.239    0.12       0 10150.8    0.12       0
#XS Ineff= 2 , 0
       0                               0
Bank Sta=9843.239,10150.8
Exp/Cntr=0.3,0.1

Type RM Length L Ch R = 1 ,28709.64,245.027000,245.027000,245.027000
XS GIS Cut Line= 6
699440.943696563864422.049743391699574.888229453864403.102529065
699732.619631773864394.598004641 699804.25978777864377.146520877
699932.565928438 864336.09232947 700029.03170029864309.179673869
#Sta/Elev= 30
9699.035199.6651 9784.09198.87069864.533196.4677 9904.61193.17679914.614188.8388
9934.621175.98369954.628165.36129964.632162.47139984.705158.5247 10005.1156.5811
10015.39160.474410035.98 170.52610046.28177.781810056.58186.439910066.89192.1495
10087.89196.816210098.39200.574110108.89204.930110119.39210.343710140.38222.2675
10161.38235.909610182.38251.386910203.35270.473210224.12288.4317 10234.5299.1286
10255.26316.465510265.64324.018710276.03328.466910286.41330.544410300.97325.8757
#Mann= 3 , 0 , 0
9699.035   0.055       09699.035   0.055       010300.97   0.055       0
#XS Ineff= 2 , 0
       0                               0
Bank Sta=9699.035,10300.97
Exp/Cntr=0.3,0.1

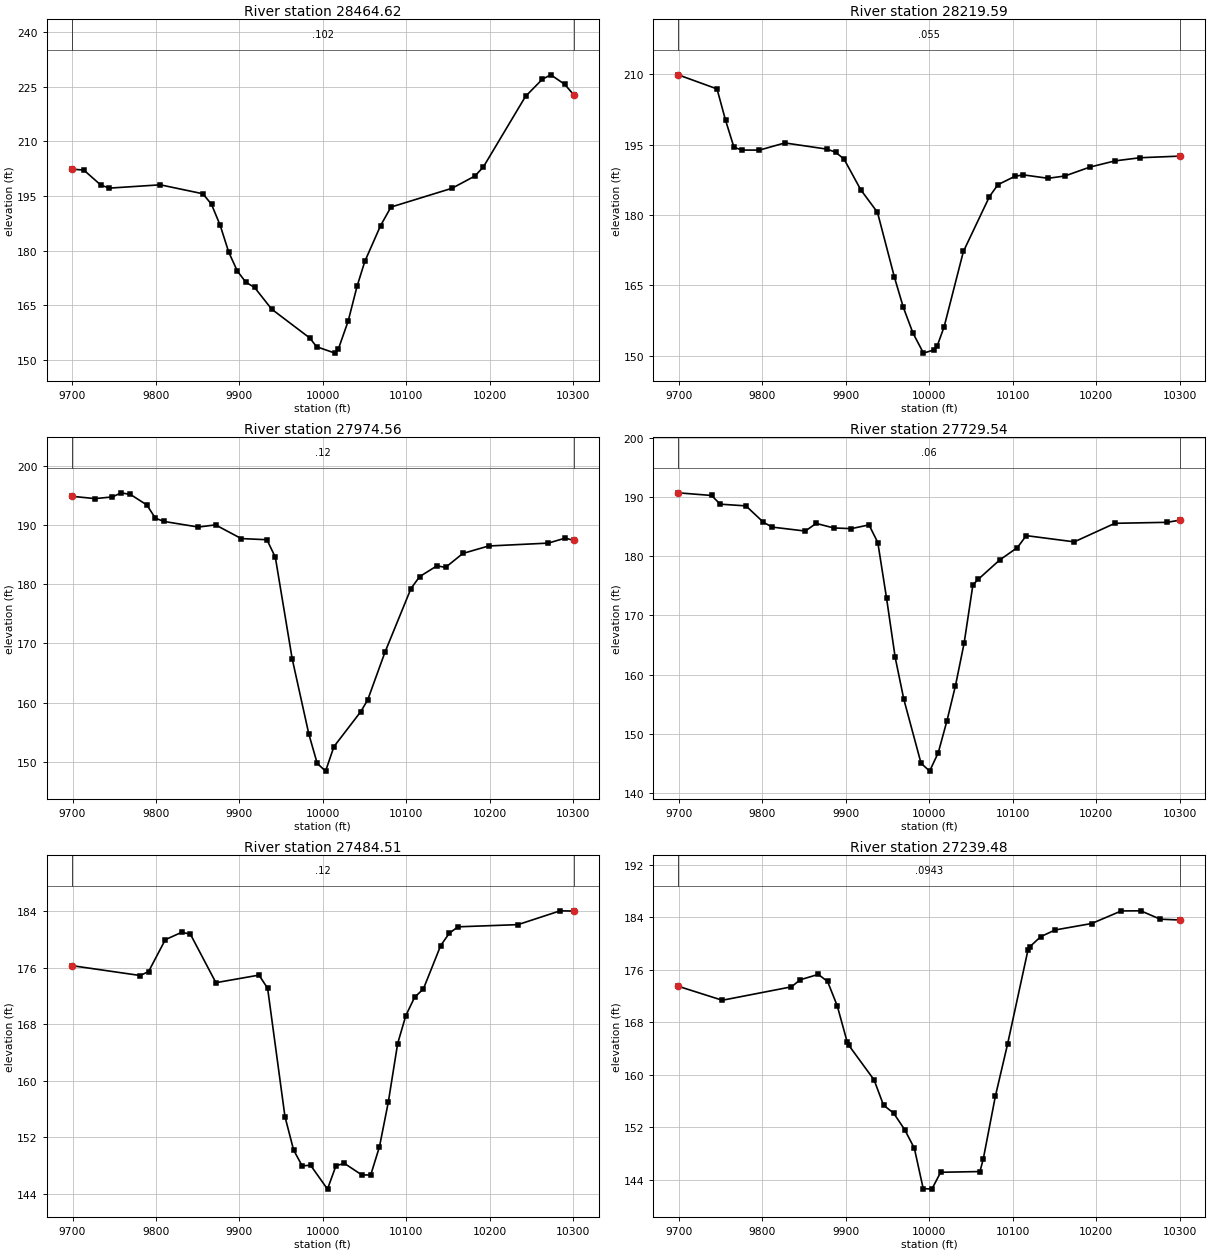
Type RM Length L Ch R = 1 ,28464.62,245.027100,245.027100,245.027100
XS GIS Cut Line= 6
699510.872517712864598.787865844699774.010068007864540.961056529
699788.138653605 864544.30828301699827.245968128864574.484757579
699862.552780738864581.735752042700092.265356872864553.374199593
#Sta/Elev= 30
 9699.14202.37519713.536202.14229733.916198.01799744.106197.17559805.245198.0813
9856.331195.62469866.634192.71359876.936186.99919887.239179.60299897.541174.4139
9907.844171.31869918.146169.92189938.752163.94019984.448156.01299992.527153.6249
10014.67151.8706 10018.7 153.02810030.37160.6476 10041.1170.2604 10050.4177.0852
10069.19186.853710081.64191.967110154.88197.1362 10182.3200.497810192.41202.9777
10242.97222.371510263.19227.0833 10273.3228.282610289.89225.680710300.87222.7676
#Mann= 3 , 0 , 0
 9699.14   0.102       0 9699.14   0.102       010300.87   0.102       0
#XS Ineff= 2 , 0
       0                               0
Bank Sta=9699.14,10300.87
Exp/Cntr=0.3,0.1

Type RM Length L Ch R = 1 ,28219.59,245.027000,245.027000,245.027000
XS GIS Cut Line= 6
699509.293594356864750.631746599699740.984578869864714.679264549
699777.264915084864723.093926999699835.519111019864761.834525084
699877.093510862864772.143191442700093.037061705864765.446735052
#Sta/Elev= 30
9699.116209.89039745.598 206.8889755.768 200.2399765.937194.41779776.107193.8463
9796.446193.84679826.955195.37189877.655194.04019887.733193.38459897.812191.9362
9917.886185.38469937.927180.57269958.295166.7105 9968.93160.30349980.387154.8681
9993.027150.561610005.24151.223810009.36152.018310017.82156.1836 10040.9172.2301
10072.11183.923710082.28186.470410102.38 188.22810112.41188.571810142.45187.8332
10162.45188.318610192.48190.218910222.52191.540710252.64192.2156 10300.9192.5632
#Mann= 3 , 0 , 0
9699.116   0.055       09699.116   0.055       0 10300.9   0.055       0
#XS Ineff= 2 , 0
       0                               0
Bank Sta=9699.116,10300.9
Exp/Cntr=0.3,0.1

Type RM Length L Ch R = 1 ,27974.56,245.027000,245.027000,245.027000
XS GIS Cut Line= 6
699517.571751766865021.601878088699740.216054253 864967.55125074
699780.547956053864962.634554363 699856.96427521864961.790663886
699982.405022518864927.450890785700104.953726725864901.184165914
#Sta/Elev= 30
9699.102194.80759727.086194.41749747.908194.70269758.198195.39229769.475195.1126
 9789.07193.3489 9799.36191.11069809.651190.56539850.813189.61969871.393189.9863
9902.265187.67639933.033187.48219943.107  184.529963.255167.43529983.303154.6773
9993.308149.759610003.33148.454910013.35152.591410045.52158.486510053.85160.4829
10074.59168.539610105.69179.254810116.06181.2606 10136.8183.076110147.16182.8161
 10167.9185.170110198.69 186.42310270.28186.912410290.73187.760210300.91 187.354
#Mann= 3 , 0 , 0
9699.102    0.12       09699.102    0.12       010300.91    0.12       0
#XS Ineff= 2 , 0
       0                               0
Bank Sta=9699.102,10300.91
Exp/Cntr=0.3,0.1

Type RM Length L Ch R = 1 ,27729.54,245.027000,245.027000,245.027000
XS GIS Cut Line= 6
699616.013142062865255.324337551699688.772607226865238.626089473
 699851.38568146865184.607485332699948.680780701865159.465504264
  700089.4479323 865107.43683256700190.264799726865077.060689187
#Sta/Elev= 30
9699.055190.74679739.055190.29749749.315188.82729780.226188.53639801.165185.7662
9811.635184.94859851.409184.27619864.318185.57299885.462184.80259906.606184.6857
 9927.75 185.3229938.322182.32449948.806172.90579959.133162.90169969.461155.8238
9990.116 144.99610000.43143.652210010.76146.7657 10021.1152.115610031.43158.1215
10041.76165.2898 10052.3175.161710058.45  176.0810084.29179.367310105.61181.4805
10116.27183.504410173.82182.450110222.51185.5883 10285.1185.755810300.96186.1337
#Mann= 3 , 0 , 0
9699.055    0.06       09699.055    0.06       010300.96    0.06       0
#XS Ineff= 2 , 0
       0                               0
Bank Sta=9699.055,10300.96
Exp/Cntr=0.3,0.1

Type RM Length L Ch R = 1 ,27484.51,245.027000,245.027000,245.027000
XS GIS Cut Line= 6
699712.937219091865407.938097057699808.056448627865408.680920572
699872.580666138865401.795758107700037.631601494865363.944357934
 700178.31137168865320.543358254700301.249086903865298.088195176
#Sta/Elev= 30
9699.056176.28169781.149174.88339791.151175.44649811.202179.95659831.273181.0214
9841.374180.70649871.844173.86769923.444174.94099933.828173.08329954.596154.9269
 9964.98150.18349975.204147.94729985.342148.027310005.62144.650810015.79147.9696
10025.97148.285110046.92146.647310057.48146.663910067.95150.672710078.47156.9382
10089.72165.252510099.51 169.20810110.03171.800310120.55172.980310141.33179.1272
10151.71180.880410162.09181.7753 10233.9182.083910284.49184.038610300.93184.0058
#Mann= 3 , 0 , 0
9699.056    0.12       09699.056    0.12       010300.93    0.12       0
#XS Ineff= 2 , 0
       0                               0
Bank Sta=9699.056,10300.93
Exp/Cntr=0.3,0.1

Type RM Length L Ch R = 1 ,27239.48,245.027000,245.027000,245.027000
XS GIS Cut Line= 6
699803.110335429865446.139067909699919.496237116865471.350830441
699996.629155024 865506.69420712700038.236148004865547.838833914
700105.600156959865659.651298653700275.908492247865775.158752939
#Sta/Elev= 30
9699.189173.50569751.978171.37499834.796173.41869845.408 174.4949866.998175.3171
 9878.15174.23889889.704170.5431 9901.63 165.0269903.573164.51579933.838159.2496
9945.196 155.3949957.314154.17559970.542151.66659982.141148.82979992.732142.6865
10003.14142.597610013.64145.165610060.76145.275310064.72147.173910079.26156.7623
 10093.8164.6568 10118.3179.022610120.18179.491310133.63 181.06510150.83182.0837
10194.67183.068110230.19184.984910253.58185.000610276.71183.727610300.88183.6012
#Mann= 3 , 0 , 0
9699.189  0.0943       09699.189  0.0943       010300.88  0.0943       0
#XS Ineff= 2 , 0
       0                               0
Bank Sta=9699.189,10300.88
Exp/Cntr=0.3,0.1

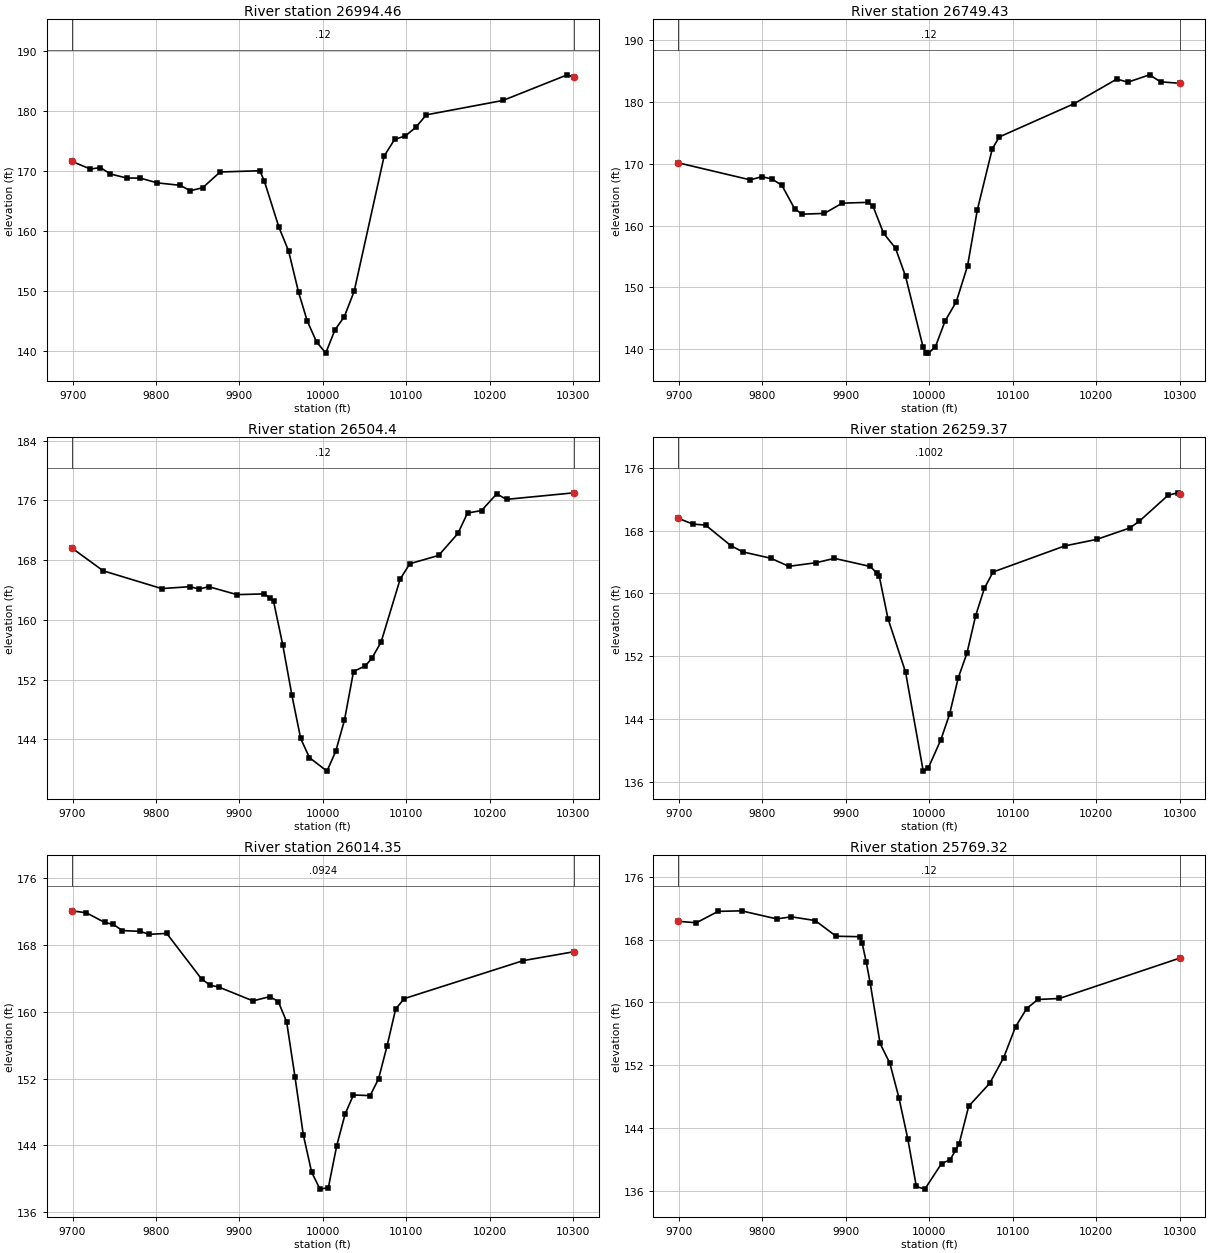
Type RM Length L Ch R = 1 ,26994.46,245.027100,245.027100,245.027100
XS GIS Cut Line= 6
699616.290738696865538.936196077699801.095817783865660.126901766
699893.363058718865707.566293382 699928.30347864865729.409111168
 699976.95895923865766.941043077700109.700431921865880.091925105
#Sta/Elev= 30
9699.046171.5782 9721.42170.30399733.378170.54319745.336169.48039764.811168.8098
9781.212168.79599801.282168.00719829.046 167.5969841.004166.69619855.988167.1947
9876.879169.81189924.528170.01949929.952168.26689947.498160.58289958.984156.6727
9970.949149.80329981.434144.99089992.473141.569110003.49139.686410014.59143.5614
 10025.8 145.75310037.59149.978210073.53172.456910086.16175.253610098.79 175.794
10111.42177.237110124.05179.312710216.02181.712810293.09185.971810300.94185.5687
#Mann= 3 , 0 , 0
9699.046    0.12       09699.046    0.12       010300.94    0.12       0
#XS Ineff= 2 , 0
       0                               0
Bank Sta=9699.046,10300.94
Exp/Cntr=0.3,0.1

Type RM Length L Ch R = 1 ,26749.43,245.027000,245.027000,245.027000
XS GIS Cut Line= 6
   699530.715558865636.743408671699590.275352639865710.914368993
699676.074372771865834.967803461699696.680950566865854.988972687
699760.544526316865901.805837213699917.570234978866093.125557946
#Sta/Elev= 30
9699.117 170.1749785.552 167.4089799.197167.92799811.258167.56069823.318166.5389
9838.498162.7597 9847.44161.84839874.275161.97659895.682163.63829926.786163.7681
9932.643 163.1269945.188158.77619959.538156.34189971.529151.81559992.581140.3175
9995.558139.3901    9999139.332610007.26140.321810019.01144.545510032.39 147.662
10045.89153.471610057.59162.524310075.54172.445210083.98174.368510173.54179.7515
10224.83183.751310237.92183.2401 10264.1184.434610277.19183.303410300.92183.0534
#Mann= 3 , 0 , 0
9699.117    0.12       09699.117    0.12       010300.92    0.12       0
#XS Ineff= 2 , 0
       0                               0
Bank Sta=9699.117,10300.92
Exp/Cntr=0.3,0.1

Type RM Length L Ch R = 1 , 26504.4,245.027000,245.027000,245.027000
XS GIS Cut Line= 6
699370.751224077865692.920715227699422.227068079865776.579356046
699467.712891819865863.608199542699495.363748841  865924.2847804
699534.096222822866027.617983742699651.131430406 866223.45577339
#Sta/Elev= 30
9699.085169.6335 9736.75166.57269806.813164.19319840.664 164.4479851.947164.1253
 9863.23 164.448 9897.04163.38399930.008163.47889937.198162.89919940.998162.4707
9951.987156.65999962.944149.92019973.475144.11499984.006141.5457   10005139.7426
10015.47142.387610025.95146.552510036.82153.085310051.05153.846810058.85154.8626
10069.87157.027510092.78165.468410104.31167.519210138.88 168.63310161.93171.5698
10173.46174.306610190.31174.648110208.44 176.87110220.23176.141610300.94 177.017
#Mann= 3 , 0 , 0
9699.085    0.12       09699.085    0.12       010300.94    0.12       0
#XS Ineff= 2 , 0
       0                               0
Bank Sta=9699.085,10300.94
Exp/Cntr=0.3,0.1

Type RM Length L Ch R = 1 ,26259.37,245.027000,245.027000,245.027000
XS GIS Cut Line= 6
699197.332447222865795.444465539699247.207108808865897.701924271
699286.875747233865988.769835171699359.376424502866204.898100882
699391.690296933866274.262561321699432.728030353866347.804153297
#Sta/Elev= 30
9699.043169.57699716.534168.84729731.926168.70819762.157166.0912 9776.43165.2953
9809.809164.49129831.683 163.4589864.405163.9167 9886.22164.46999929.304163.4371
9937.203162.58199939.876162.27629950.447156.79679971.589 149.9549992.731137.3349
9998.885137.751910013.88141.3391 10024.3144.587210034.72149.225910045.15152.3793
10055.57157.156810065.99160.636310076.41162.729310162.38166.056910200.88166.8951
10240.47168.350210251.92169.222910286.28172.517810297.73172.829510300.94172.7112
#Mann= 3 , 0 , 0
9699.043  0.1002       09699.043  0.1002       010300.94  0.1002       0
#XS Ineff= 2 , 0
       0                               0
Bank Sta=9699.043,10300.94
Exp/Cntr=0.3,0.1

Type RM Length L Ch R = 1 ,26014.35,245.027000,245.027000,245.027000
XS GIS Cut Line= 6
699015.249093042865849.075960848699080.473307315866042.710763059
699086.436111543866183.892303303699097.583561013866243.291010755
 699127.43637565866318.583729679699186.503822128866415.701547005
#Sta/Elev= 30
9699.067172.10169716.463171.8706 9738.31170.71929748.998170.46789759.685169.7331
9781.061169.63939791.748 169.282 9812.88169.39399854.673163.9254 9864.97163.1892
9875.266162.96619916.263 161.306 9936.52161.81739946.558161.23199956.597 158.814
 9966.62152.20349976.624145.24279986.627140.76339996.631138.740810006.64138.9176
10016.66143.938510026.67147.728810036.67150.023510056.77149.954210066.85151.9726
10077.02155.910110087.29 160.32310097.56 161.57510240.36166.136110300.91167.1972
#Mann= 3 , 0 , 0
9699.067  0.0924       09699.067  0.0924       010300.91  0.0924       0
#XS Ineff= 2 , 0
       0                               0
Bank Sta=9699.067,10300.91
Exp/Cntr=0.3,0.1

Type RM Length L Ch R = 1 ,25769.32,245.027000,245.027000,245.027000
XS GIS Cut Line= 6
698639.737611071866020.968545757698800.903653062866178.051461704
698842.640860218866200.466263924 698901.13771245 866210.27573715
698935.203451289866233.365980651 699082.34711795866407.556671311
#Sta/Elev= 30
9699.096170.34849720.838 170.1629746.882171.61589774.965171.6849 9817.09170.6551
9834.796170.92019863.258170.4427 9888.34168.44339916.666168.38459919.493167.5795
9924.303165.21519929.154162.48789940.995 154.7829952.719152.2431 9963.56147.8661
 9974.26142.58149984.501136.52279994.632136.184410014.69139.445110025.02139.9351
 10031.4141.126510035.81141.992110047.22146.757710072.44149.685110089.21152.9729
10103.39156.890610116.74159.216810130.06160.376710155.93160.502510300.88165.6763
#Mann= 3 , 0 , 0
9699.096    0.12       09699.096    0.12       010300.88    0.12       0
#XS Ineff= 2 , 0
       0                               0
Bank Sta=9699.096,10300.88
Exp/Cntr=0.3,0.1

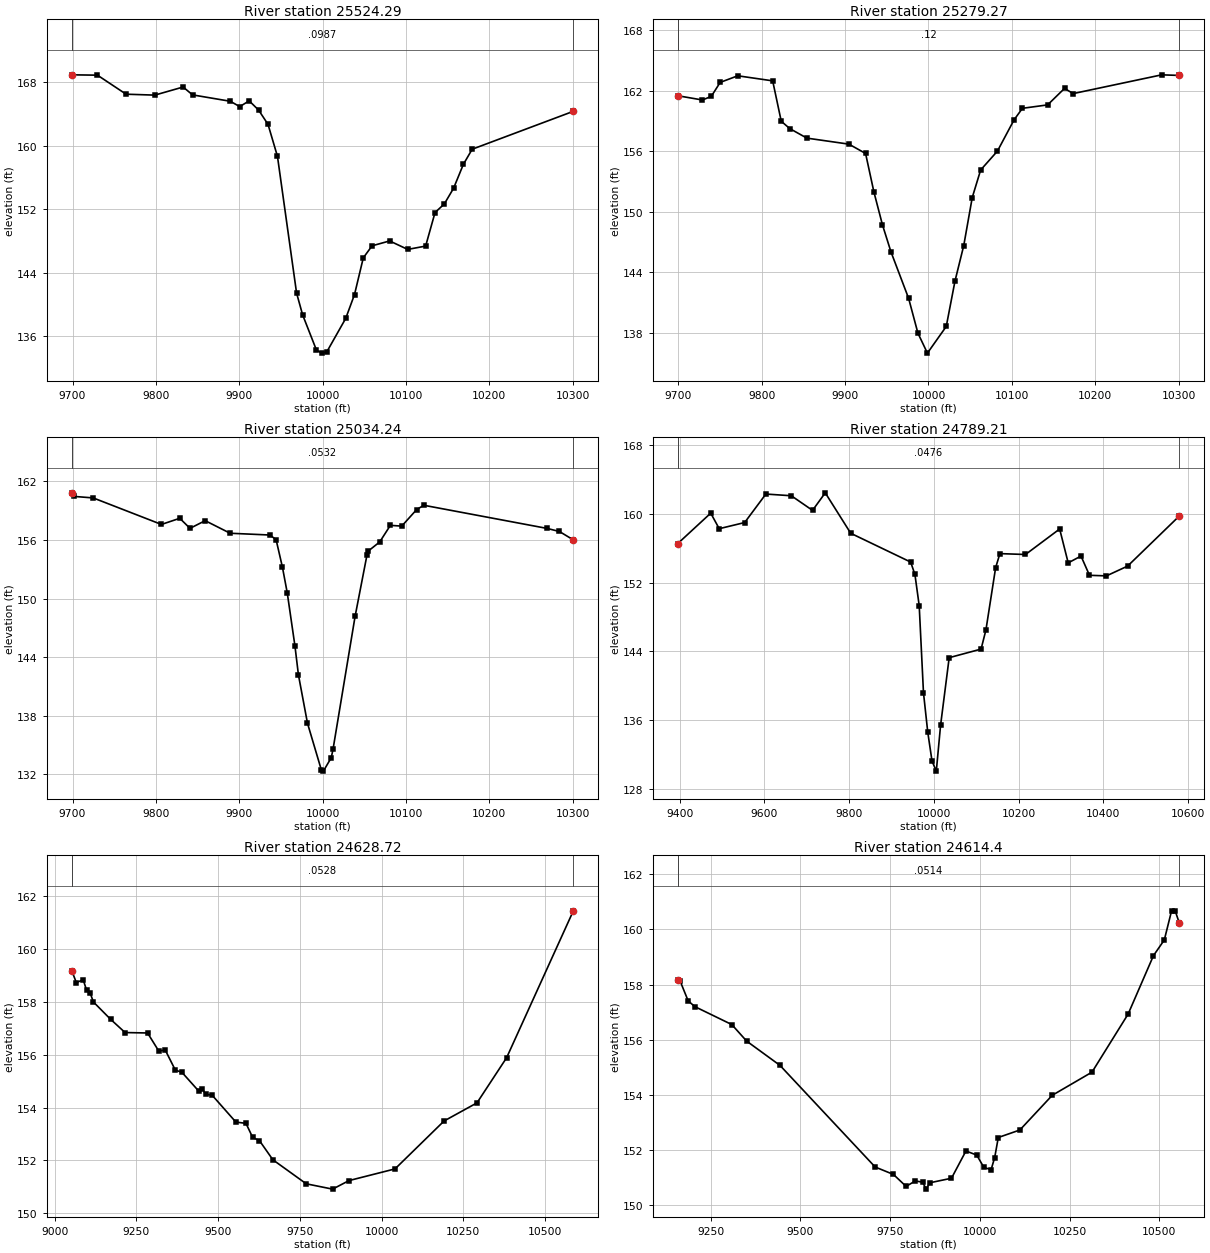
Type RM Length L Ch R = 1 ,25524.29,245.027100,245.027100,245.027100
XS GIS Cut Line= 6
698448.094143611866212.322775719698676.846308932866336.392655824
698725.834860331 866368.88856317698784.454334817866388.221255624
698823.875896245866404.507457842698982.401757098866486.131556898
#Sta/Elev= 30
9699.026168.90499729.861168.86189764.241166.46529798.622166.34929832.666167.3698
9843.986166.37839889.265165.57569900.585164.90119911.905 165.6299923.225 164.467
9934.545162.65979945.865  158.639968.792141.41969975.963138.70199992.605134.2461
    9999133.8576 10005.1134.025910027.78138.236710038.31141.240310048.84145.8592
10059.37147.373110080.45147.985510102.09146.920410123.63147.336910134.91151.5631
10146.06 152.647 10157.2154.628910168.91157.632210179.49 159.53610300.86164.3107
#Mann= 3 , 0 , 0
9699.026  0.0987       09699.026  0.0987       010300.86  0.0987       0
#XS Ineff= 2 , 0
       0                               0
Bank Sta=9699.026,10300.86
Exp/Cntr=0.3,0.1

Type RM Length L Ch R = 1 ,25279.27,245.027000,245.027000,245.027000
XS GIS Cut Line= 6
698447.120494855866556.965513923698644.013089183866608.524817215
698698.481891034866602.326807251698778.103979016866567.966173752
  698855.7665601 866565.11808628699024.139094643866617.809263686
#Sta/Elev= 30
9699.145161.51099728.816161.08859739.458161.44599750.101162.8303  9771.2163.4849
9813.084162.9847 9823.37158.98149833.626158.25359854.138157.3103 9904.51 156.714
9924.529155.79189934.553151.96519944.753148.72589954.953146.0486 9976.17141.4348
9987.304137.99139998.692136.0105 10021.3138.6524 10031.8143.159410042.28146.6656
10052.48151.425710062.55154.152810082.68156.024410102.69159.128710112.69160.2646
10142.91160.603110163.18 162.23810173.52161.721510279.79163.581110300.82163.5216
#Mann= 3 , 0 , 0
9699.145    0.12       09699.145    0.12       010300.82    0.12       0
#XS Ineff= 2 , 0
       0                               0
Bank Sta=9699.145,10300.82
Exp/Cntr=0.3,0.1

Type RM Length L Ch R = 1 ,25034.24,245.027000,245.027000,245.027000
XS GIS Cut Line= 6
698432.132393577866613.816317769 698505.24152393866651.909851881
698569.766091264866694.964848891698746.050217537866873.307684381
698808.143577446866922.278768291698901.085195813 866984.28302538
#Sta/Elev= 30
 9699.08160.83679702.313 160.4679724.866 160.3149806.703157.5989 9828.69158.2278
9840.986157.19899859.194157.98589889.155156.69659936.864 156.5159944.264156.0453
9951.887153.21659957.665150.58979966.909145.14619971.065142.19769981.932137.2409
9998.553132.4621   10001 132.33410010.46133.708510012.65 134.60310039.04148.1721
10053.33154.468310054.65154.858710068.64155.809610081.39 157.50610095.04 157.427
10112.87159.116510121.53159.562810269.58157.189110284.21156.876910300.94 156.017
#Mann= 3 , 0 , 0
 9699.08  0.0532       0 9699.08  0.0532       010300.94  0.0532       0
#XS Ineff= 2 , 0
       0                               0
Bank Sta=9699.08,10300.94
Exp/Cntr=0.3,0.1

Type RM Length L Ch R = 1 ,24789.21,160.490700,160.490700,160.490700
XS GIS Cut Line= 6
697907.103192925866891.883001417698394.182157815866913.400546059
698550.407055169866939.682724625698644.229166687866982.145543054
698846.773331821867006.900362521 699076.80805403867013.410779163
#Sta/Elev= 30
9395.384156.55629473.357160.11159493.377158.29879553.435159.01549603.484 162.337
9663.542 162.1379713.591160.4337 9743.62162.47879803.679157.76659945.126154.4112
9955.213152.96419965.301149.33239975.388139.18359985.475134.58859995.563131.2123
10005.66130.044910015.78135.406410036.03 143.26710111.33144.268110122.79146.5082
10145.61153.745410155.69155.394210216.13155.291610296.73158.264110316.88154.3164
 10347.1155.109110367.12152.866610407.14152.799410457.16153.942310579.01159.7734
#Mann= 3 , 0 , 0
9395.384  0.0476       09395.384  0.0476       010579.01  0.0476       0
#XS Ineff= 2 , 0
       09906.447        10184.18       0
Bank Sta=9395.384,10579.01
Exp/Cntr=0.3,0.1

Type RM Length L Ch R = 1 ,24628.72,14.325900,14.325900,14.325900
XS GIS Cut Line= 6
697581.582359582866887.542723626697852.849720716866970.008001417
698234.794165134867063.323973641698493.040692925867093.705918059
698699.203887403867091.535779193699087.658748478867045.962862521
#Sta/Elev= 30
9052.396159.1725 9066.42158.71939087.323158.82749097.775158.43439108.227158.3411
9118.679157.98769170.938157.33649215.559156.83259284.321156.81669318.703156.1308
9338.134156.17779369.017155.41789389.605155.32739441.076154.6176 9451.37154.7155
9461.664154.50699482.252154.45979554.311153.45179585.193153.40299605.782152.8706
 9626.37 152.7529667.546152.02669769.582151.11979850.134150.91879900.479151.2421
10041.09151.6829 10191.1153.492610291.75154.177210382.37155.882210586.42161.4302
#Mann= 3 , 0 , 0
9052.396  0.0528       09052.396  0.0528       010586.42  0.0528       0
#XS Ineff= 2 , 0
       09839.971        10146.22       0
Bank Sta=9052.396,10586.42
Exp/Cntr=0.3,0.1

Type RM Length L Ch R = 1 , 24614.4,89.183400,89.183400,89.183400
XS GIS Cut Line= 6
697678.804581821 866947.87258473697973.075415164867022.091334745
698333.752498478867091.101751402698470.471248507867106.726751402
698725.679581851867100.216334745699056.408748478867061.153834745
#Sta/Elev= 30
9158.316158.16519164.706 158.1429187.461 157.4129205.958157.2032 9309.09156.5518
9350.343155.95359443.161155.07419708.289151.39139759.196151.12229794.509150.6886
9820.155150.88739840.368150.84229850.433  150.599860.498150.81999920.889150.9844
9961.149151.97249991.201151.823410011.21151.374410031.23151.296910041.23151.7336
10051.24152.460310111.34152.732610201.57  153.9910312.25154.828710412.94156.9348
10483.43159.049610513.64159.618910533.78160.668810543.85160.672910555.33160.2349
#Mann= 3 , 0 , 0
9158.316  0.0514       09158.316  0.0514       010555.33  0.0514       0
#XS Ineff= 2 , 0
       09846.682        10141.64       0
Bank Sta=9158.316,10555.33
Exp/Cntr=0.3,0.1

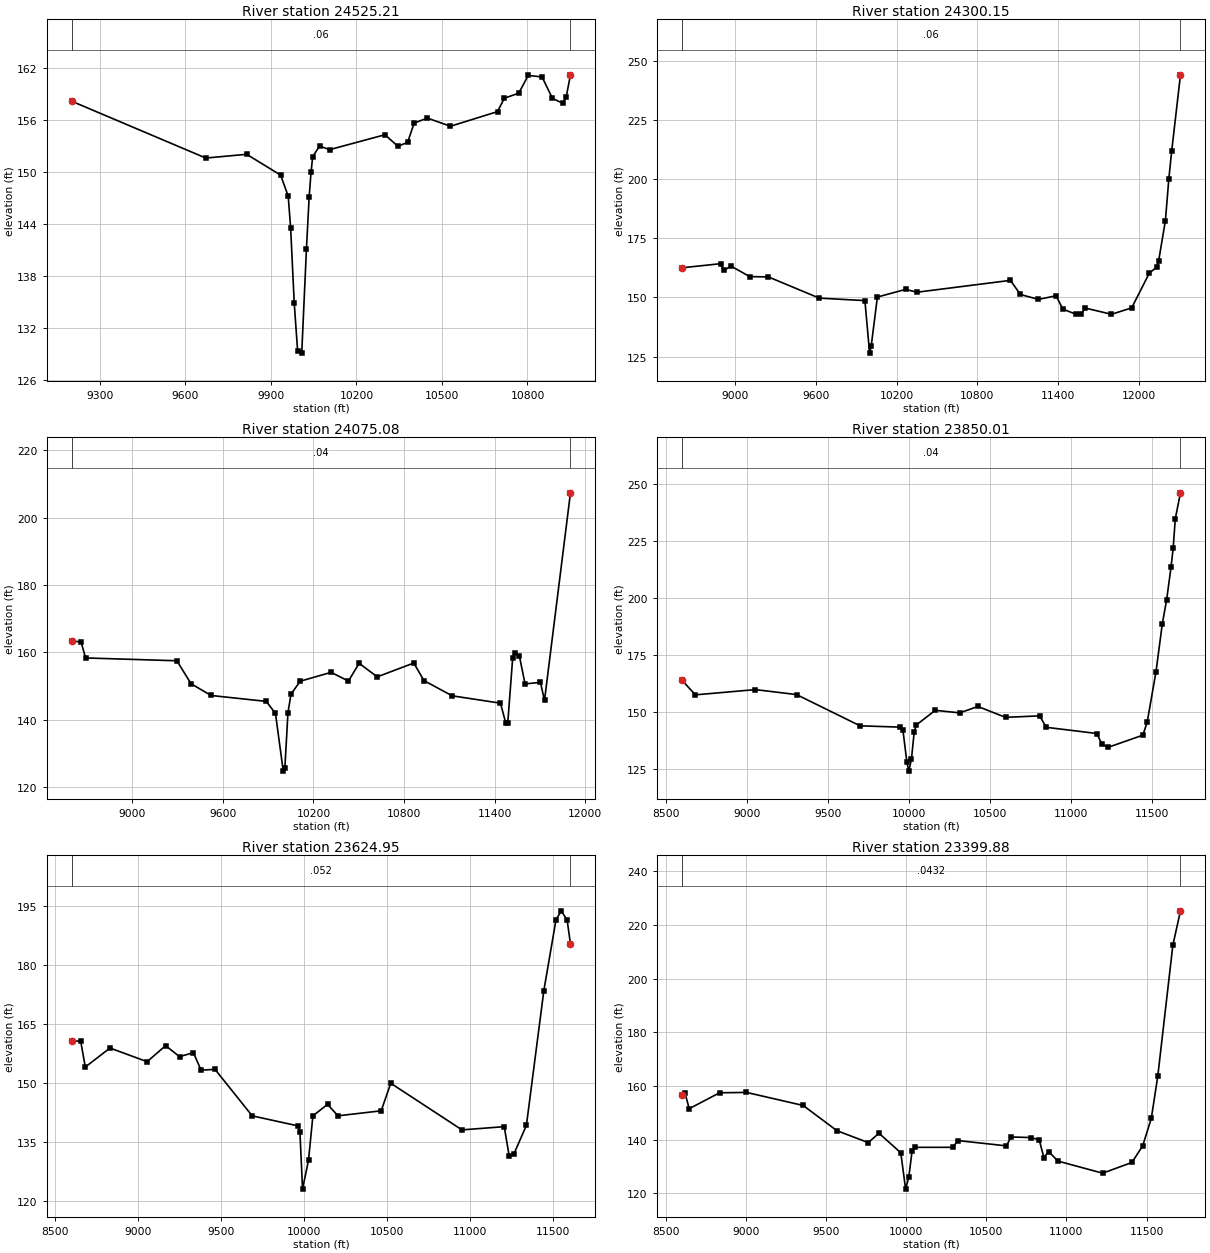
Type RM Length L Ch R = 1 ,24525.21,225.066100,225.066100,225.066100
XS GIS Cut Line= 6
697711.790692955866993.879529193698065.523331851867052.473279193
698379.320502996 867129.44766967698540.545755655867235.459796026
698956.518915862867469.883484706699287.313945383867687.314714804
#Sta/Elev= 30
9200.993158.12119671.739151.56449815.043151.99459934.206149.59539960.791147.1648
 9969.29143.49779981.823134.87369993.704129.337810008.19129.069610024.76141.1245
10034.27147.091610040.77149.907110046.57151.712310070.69152.951210105.69152.5303
10299.96154.250110345.51152.921510379.67153.378510402.56155.600510448.89156.1697
10529.98155.2314 10694.9156.917510718.74158.456110769.32159.046810802.75161.0932
10851.17160.915510887.49158.451110923.81157.872910935.92158.618410950.83161.1601
#Mann= 3 , 0 , 0
9200.993    0.06       09200.993    0.06       010950.83    0.06       0
#XS Ineff= 2 , 0
       0 9864.96        10066.15       0
Bank Sta=9200.993,10950.83
Exp/Cntr=0.3,0.1

Type RM Length L Ch R = 1 ,24300.15,225.066200,225.066200,225.066200
XS GIS Cut Line= 6
697173.179807484866587.300993979697455.004787743866821.130270824
697774.962935776867047.158858389698746.154102147867566.178935945
699012.441090614 867732.56892319700244.304738194868654.553064197
#Sta/Elev= 30
8599.039162.53318888.909164.27978914.372161.41228965.298163.29439105.963158.8161
9244.696158.69319623.743149.70919963.231148.66359998.297126.433710009.96129.3641
10056.26150.177310266.38153.406110350.79152.210911046.35 157.22711120.34151.2607
11253.93149.180911386.28150.697611435.91145.108411534.55 142.84511572.21142.8007
11601.34145.534811798.16142.873411948.75145.575112081.09160.392412137.09162.8189
12149.65165.553912199.86182.550512224.96199.951912246.53211.971312311.96 244.211
#Mann= 3 , 0 , 0
8599.039    0.06       08599.039    0.06       012311.96    0.06       0
#XS Ineff= 2 , 0
       0                10204.58       0
Bank Sta=8599.039,12311.96
Exp/Cntr=0.3,0.1

Type RM Length L Ch R = 1 ,24075.08,225.066100,225.066100,225.066100
XS GIS Cut Line= 6
697187.832276016866802.149482638697997.228788376867464.214677766
698220.992884785867569.305162832698470.428474218867568.316894218
 698716.33612749867686.213923454 699901.49061057868571.047058761
#Sta/Elev= 30
8599.215163.52188662.404163.03168691.896158.3799 9296.16157.53949389.615150.7358
9522.457147.24259887.721145.49129948.731141.918510000.24124.800210010.94125.7391
10031.49142.190910051.63147.628510112.03151.468910316.87154.1041 10431.9151.5209
10502.51156.792610622.37152.772110864.57 156.87810931.49151.663811118.53147.1425
11437.97144.963911473.96138.972611486.59139.1699   11519158.351611535.21159.9579
11562.91159.035811601.03150.678211702.69151.137311729.69145.772611901.55207.3653
#Mann= 3 , 0 , 0
8599.215    0.04       08599.215    0.04       011901.55    0.04       0
#XS Ineff= 2 , 0
       09710.504        10154.74       0
Bank Sta=8599.215,11901.55
Exp/Cntr=0.3,0.1

Type RM Length L Ch R = 1 ,23850.01,225.066100,225.066100,225.066100
XS GIS Cut Line= 6
697140.496215492866806.097775042697549.831513584867182.918304205
698150.450514406867695.388444096698232.410908133867752.851503327
698520.150664598868027.333450541699448.800160021868834.750233844
#Sta/Elev= 30
8599.042164.0156 8683.92157.42519053.414159.72899307.415157.5501 9698.87 143.845
9944.489143.2728 9963.31141.80589987.621127.84129999.377123.968110015.59129.2601
10032.59141.160110045.29144.181310162.12150.639510313.81149.522810424.79152.3392
 10595.5147.5582 10805.6148.213210846.51143.186911158.54140.474111189.23135.7763
11228.84134.436611441.64139.742911468.33145.424211523.02167.662711561.77188.6744
11588.46199.150811615.16213.3304 11628.5221.673311641.85234.766811673.62246.0524
#Mann= 3 , 0 , 0
8599.042    0.04       08599.042    0.04       011673.62    0.04       0
#XS Ineff= 2 , 0
       09756.934        10172.47       0
Bank Sta=8599.042,11673.62
Exp/Cntr=0.3,0.1

Type RM Length L Ch R = 1 ,23624.95,225.066100,225.066100,225.066100
XS GIS Cut Line= 6
697073.220244765866835.647790879697752.328786105867515.270213619
698183.746725589868072.830374286698323.183972836868233.137980744
698535.566694498868443.927862078699149.936561614869001.762244731
#Sta/Elev= 30
8599.051160.62718653.766 160.6298681.574154.02748830.509158.86649054.267155.3926
9165.937159.46879249.689156.67479333.442157.68399379.696 153.2469463.824153.4379
9687.908141.63799962.772139.09459975.706137.52749991.493123.021110027.71130.4359
10053.86141.630410142.15144.560110205.11141.641510465.66142.917610523.47149.9176
10952.79138.069611207.62138.8892 11237.2131.497211266.79132.051311341.27139.2071
11446.49173.4753   11520191.512911551.72193.717311586.97191.342611606.98185.2927
#Mann= 3 , 0 , 0
8599.051   0.052       08599.051   0.052       011606.98   0.052       0
#XS Ineff= 2 , 0
       09804.587        10115.72       0
Bank Sta=8599.051,11606.98
Exp/Cntr=0.3,0.1

Type RM Length L Ch R = 1 ,23399.88,225.066200,225.066200,225.066200
XS GIS Cut Line= 6
696991.083678454866849.941918671697705.025380224867646.051992446
 697810.22764945867843.892776266697841.429824442868049.391317427
697980.562456936868270.083239853698921.393809855869230.304996461
#Sta/Elev= 30
8599.149156.72628619.482157.57318646.489151.56698835.533 157.4899003.367157.6385
9357.454152.77289568.253 143.3729763.584138.93239830.258142.42599966.548135.1492
9996.616121.598310016.69126.200310036.74135.638510054.75137.178410290.12137.1765
 10323.4139.688610625.74 137.717 10654.1 141.03610779.41140.811110830.32139.9408
10859.41133.346210888.71135.602110947.32132.043511225.73127.5371 11408.7131.5406
 11475.9137.744311529.65148.000711569.97163.719711664.04212.525711711.49225.2976
#Mann= 3 , 0 , 0
8599.149  0.0432       08599.149  0.0432       011711.49  0.0432       0
#XS Ineff= 2 , 0
       0 9838.73         10130.4       0
Bank Sta=8599.149,11711.49
Exp/Cntr=0.3,0.1

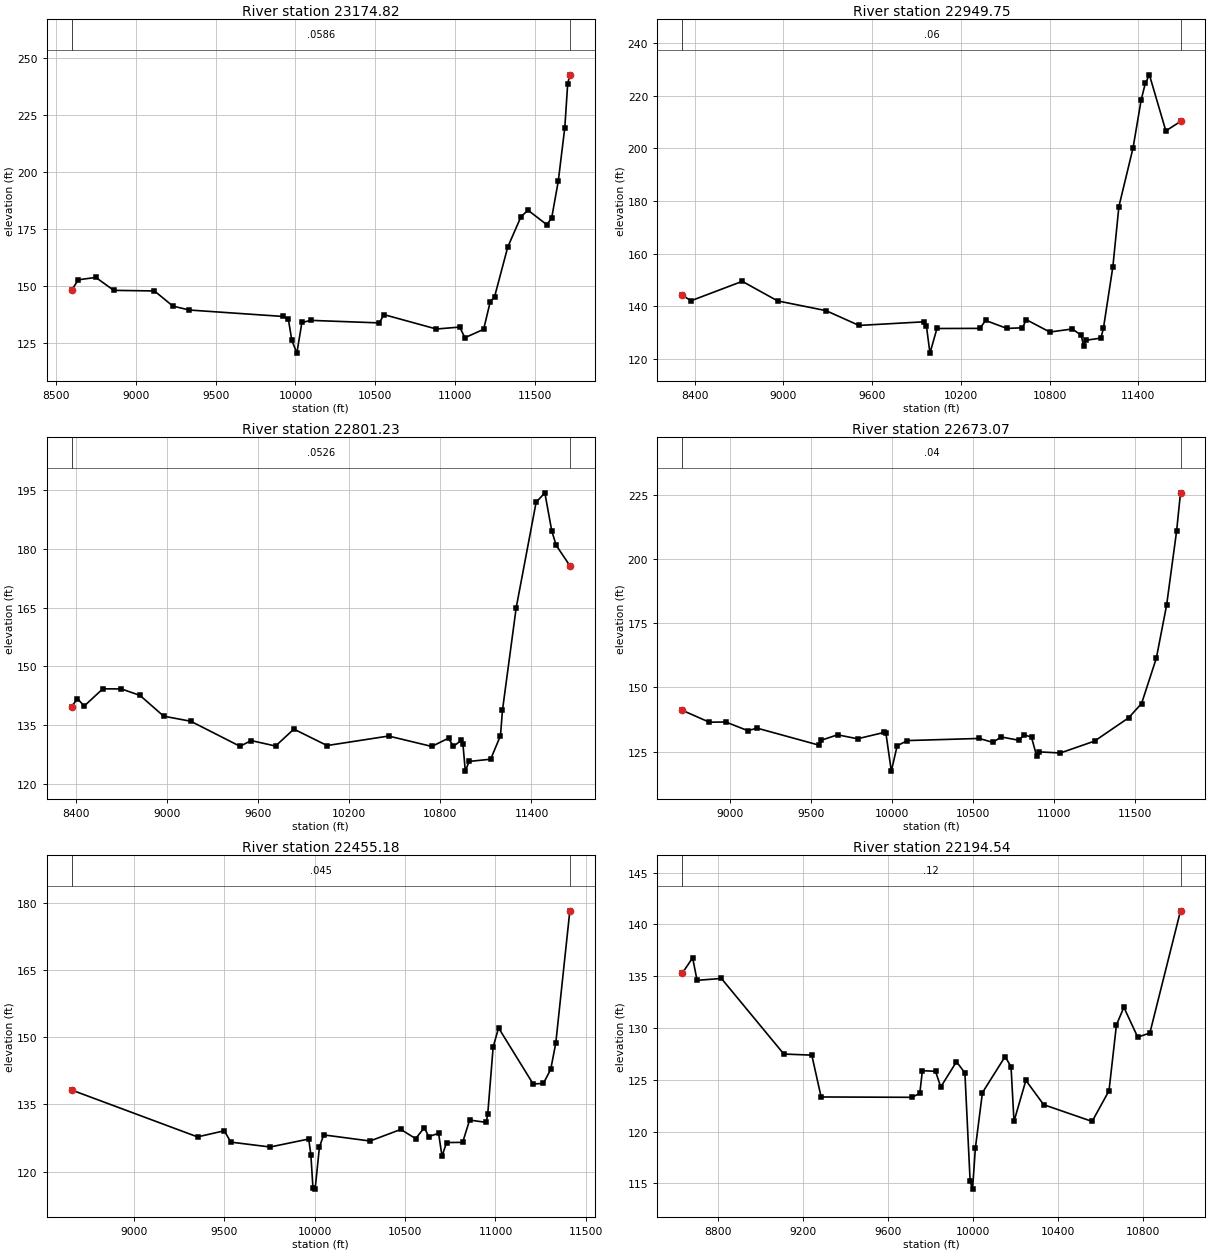
Type RM Length L Ch R = 1 ,23174.82,225.066100,225.066100,225.066100
XS GIS Cut Line= 6
696809.732037693 866932.94688949697521.115294099867848.804812476
697670.447049767868130.725562826697743.587644875868231.308606401
697957.733294785868456.471609205698837.887804419869274.255525649
#Sta/Elev= 30
8599.088148.05828641.814152.61528750.446153.65678863.286147.97939117.456147.7246
9232.919141.08539335.552139.35199922.106136.53489955.364135.35459977.063126.1297
10008.55120.446910040.25133.886210096.91134.811510525.23133.702510552.63137.3602
10881.61 131.02111027.87131.875511059.82127.209411177.36130.885511218.47142.9401
11245.87145.203711328.11166.950511411.54180.3699 11455.3  183.1211571.97176.8198
11602.87179.670711644.08195.733111685.29219.406411703.24238.505111716.73242.5227
#Mann= 3 , 0 , 0
8599.088  0.0586       08599.088  0.0586       011716.73  0.0586       0
#XS Ineff= 2 , 0
       09875.351        10107.21       0
Bank Sta=8599.088,11716.73
Exp/Cntr=0.3,0.1

Type RM Length L Ch R = 1 ,22949.75,148.522900,148.522900,148.522900
XS GIS Cut Line= 6
696507.684365056866874.842201542696886.776764827867575.258529814
697145.576993876 867920.00867457697334.484535197868099.769853644
698091.978495733868694.173491056698766.256490305869312.923653805
#Sta/Elev= 30
8315.714144.14168375.597142.07218721.319149.43928960.651141.99879287.643138.2984
9510.807132.67169948.333134.04479966.834132.29159990.474122.1411 10037.7131.5065
10327.74 131.553 10366.7134.555210510.84131.533110615.68131.778910641.88134.8626
10800.69130.157410953.03131.332511013.94128.870811028.87124.7507 11043.8127.0236
11146.21127.856611163.26131.6069   11227154.968611267.86177.897611363.56200.2004
11418.36218.447911446.17224.673811473.98227.968611585.22 206.646 11684.3210.2439
#Mann= 3 , 0 , 0
8315.714    0.06       08315.714    0.06       0 11684.3    0.06       0
#XS Ineff= 2 , 0
       09875.878        10098.88       0
Bank Sta=8315.714,11684.3
Exp/Cntr=0.3,0.1

Type RM Length L Ch R = 1 ,22801.23,128.157500,128.157500,128.157500
XS GIS Cut Line= 6
696483.528204739867040.264204025696931.444871396867953.458648488
697285.611538112868269.430870712697664.083760321868467.347537383
698473.111538082869130.541981816698705.750426978869345.819759592
#Sta/Elev= 30
8370.648139.73718409.337141.7548 8453.89139.8841 8576.41144.28038698.929144.2492
8821.449 142.5928977.383137.29019155.594135.99919480.221129.59649553.358131.0662
9714.173129.66889834.785133.989510053.56129.795810458.79132.221910743.26129.5625
10853.66131.680410885.21129.576610937.21131.0939 10948.3 130.24110964.08123.2613
10988.94 125.73411131.17126.307511195.82132.341111208.75138.805311299.27164.9869
11430.52191.922911488.06194.328711533.59184.576411563.03180.907911652.58175.7294
#Mann= 3 , 0 , 0
8370.648  0.0526       08370.648  0.0526       011652.58  0.0526       0
#XS Ineff= 2 , 0
       09885.873         10108.8       0
Bank Sta=8370.648,11652.58
Exp/Cntr=0.3,0.1

Type RM Length L Ch R = 1 ,22673.07,217.889800,217.889800,217.889800
XS GIS Cut Line= 6
696546.486517072867438.048790917696851.611462116868009.271071702
697185.120122939868364.067519411697472.505245566868498.890169531
697912.452840716868825.302901417 698728.48467043869520.703938916
#Sta/Elev= 30
8707.189 141.0578873.791136.43448975.826136.50629111.873133.12599168.559134.1145
9549.551127.50949564.151129.40779664.597131.51289788.117 129.978 9952.06132.4534
9963.106132.05319996.243117.385210032.29127.264210095.66129.278910538.65130.1061
10622.56128.559710672.91 130.69210783.61129.386810815.44131.5843 10860.7  130.53
10891.53123.412210906.95124.8721 11038.8124.451511249.01129.070611459.23138.1335
11539.07143.701211630.03 161.32211693.25181.913511754.92210.716111779.13225.7011
#Mann= 3 , 0 , 0
8707.189    0.04       08707.189    0.04       011779.13    0.04       0
#XS Ineff= 2 , 0
       09925.732        10118.01       0
Bank Sta=8707.189,11779.13
Exp/Cntr=0.3,0.1

Type RM Length L Ch R = 1 ,22455.18,260.641100,260.641100,260.641100
XS GIS Cut Line= 6
696517.374018699867539.796889901696585.328026384 867742.67809923
697127.476667464868546.219835192697668.743670523868840.651601121
697880.535795927868979.943758726698397.122270077869450.595897883
#Sta/Elev= 30
8657.027138.20859353.144 127.7569501.075129.11679537.265126.59049754.404125.5032
9967.665127.27979979.509 123.8049991.353116.2536 10003.2116.109810026.88125.4914
10050.57128.202810306.45126.838810476.63129.420510558.88127.366710606.63129.8286
 10630.9127.8129 10685.5128.561310704.51123.441610729.44126.497510818.49126.5326
10857.01131.508310948.69130.991310957.25132.875210987.12147.801111016.98152.0603
11208.25139.551911264.82139.684611305.29142.816511333.25 148.66611410.97178.1611
#Mann= 3 , 0 , 0
8657.027   0.045       08657.027   0.045       011410.97   0.045       0
#XS Ineff= 2 , 0
       09925.605        10079.16       0
Bank Sta=8657.027,11410.97
Exp/Cntr=0.3,0.1

Type RM Length L Ch R = 1 ,22194.54,723.548200,723.548200,723.548200
XS GIS Cut Line= 6
696516.125876993867648.041523829696578.842317969867863.279820174
696851.435000807868468.094835192697102.795982122 868814.97298938
697188.266138345868872.962994352697835.810000807 869535.80316852
#Sta/Elev= 30
8632.131135.28888681.042136.78118701.874134.60418816.449134.78489110.488127.4835
9242.113127.37749285.988123.33629713.268123.30399750.545123.68249762.895125.8777
9824.642 125.8169849.341124.30459923.438126.74389963.016125.65189987.611115.1918
    9999114.434310012.35118.404810045.57123.757410152.22127.234110180.18126.2629
10194.16120.980110250.08124.937910333.96122.5915   10562120.974210641.51123.9397
10676.48130.287410711.41132.002610776.65129.116910833.89129.513910978.16 141.318
#Mann= 3 , 0 , 0
8632.131    0.12       08632.131    0.12       010978.16    0.12       0
#XS Ineff= 2 , 0
       09923.848        10131.95       0
Bank Sta=8632.131,10978.16
Exp/Cntr=0.3,0.1