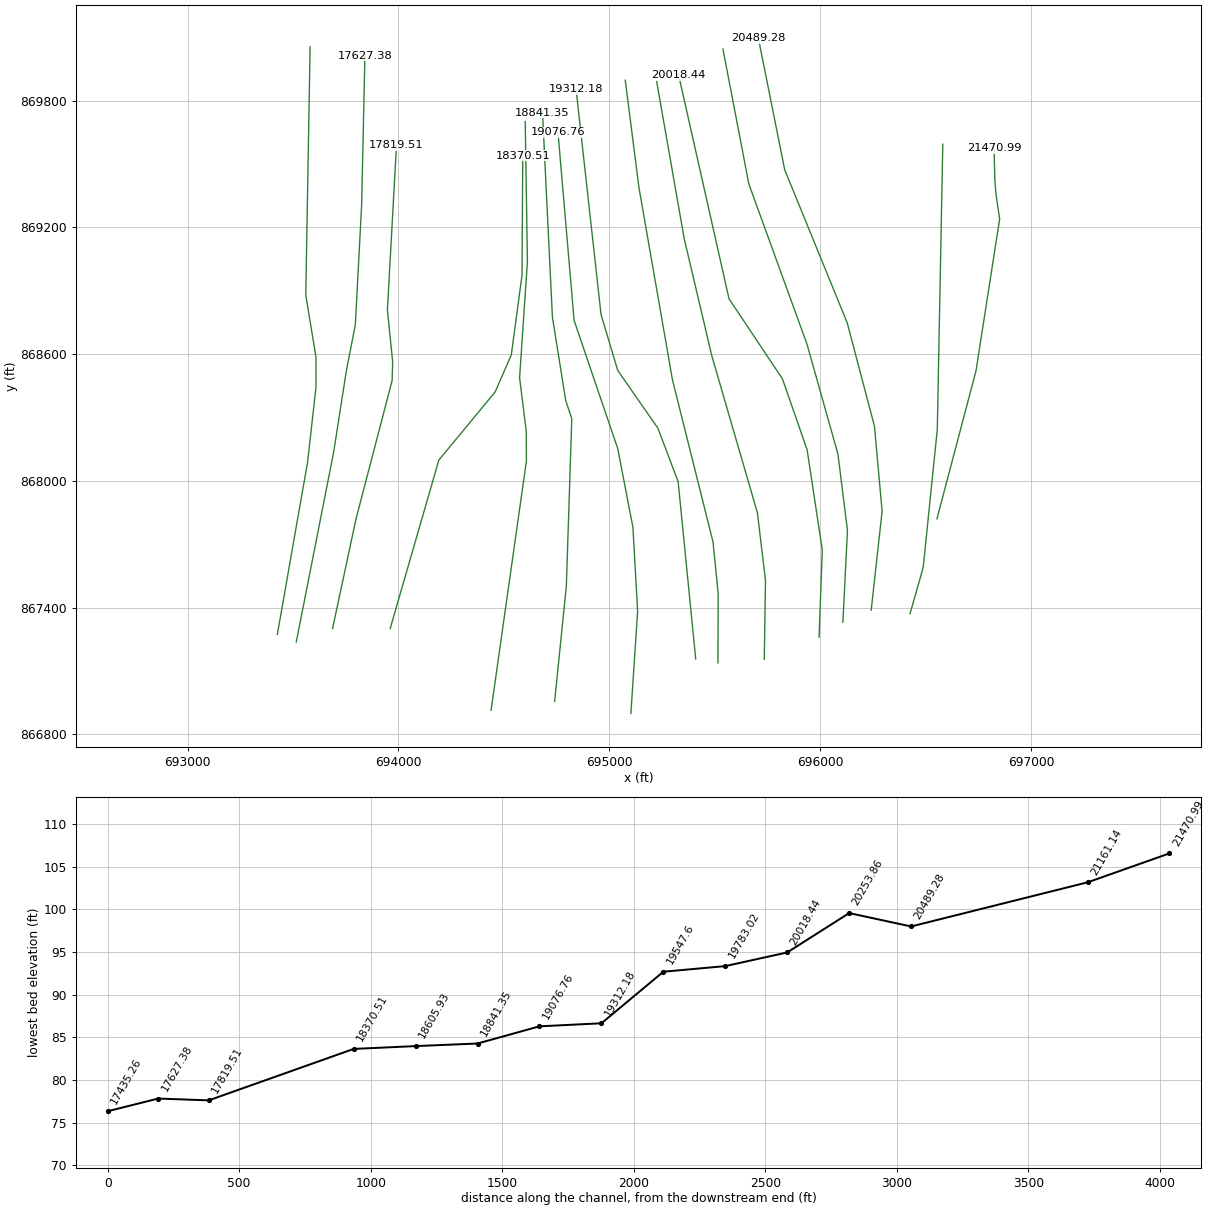
HEC-RAS study 13600_ras.prj: 13600

--- 13600_ras.g01 (geometry) --- (continued)

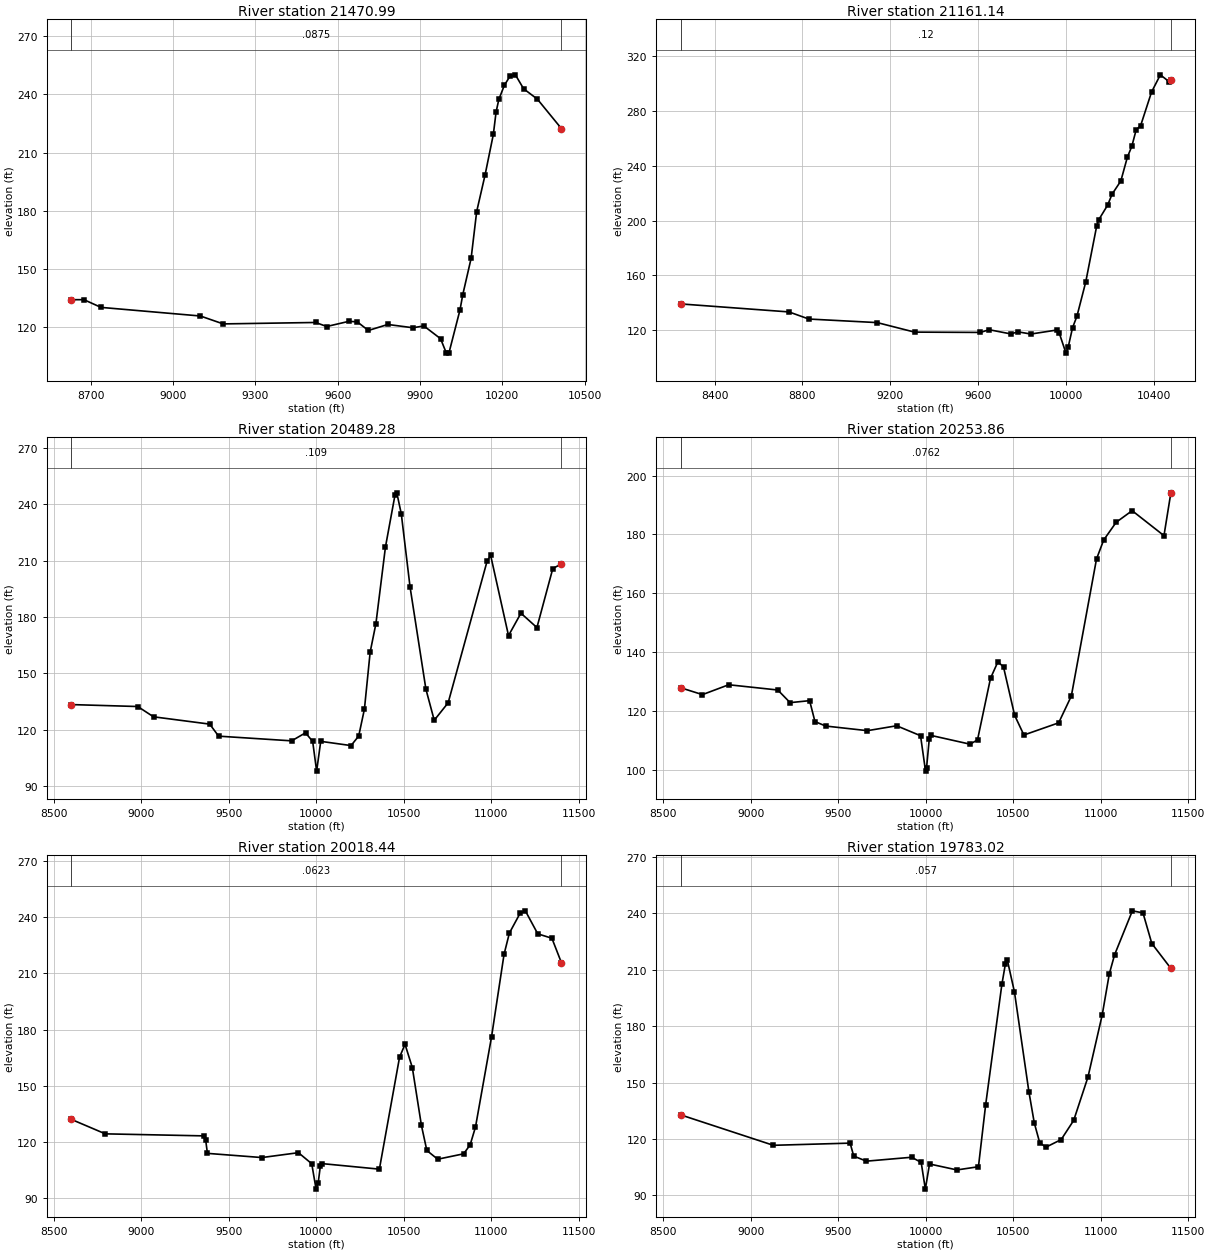
Type RM Length L Ch R = 1 ,21470.99,309.848900,309.848900,309.848900
XS GIS Cut Line= 6
696552.855049103867820.030114621696737.939006776868520.007848501
696850.114547133869238.762236804696832.768914938869355.300804347
696827.218405634869424.341209963696823.841981918869572.969407961
#Sta/Elev= 30
8628.267134.11248674.825134.11048736.943 130.1429099.108125.69899182.378121.6141
9519.297122.35369559.781120.27369640.749122.95069671.112 122.6729711.597118.2254
9782.444121.32459873.534119.63579914.018120.54919974.744 113.9789994.986106.8543
10005.11106.538710045.59128.851710055.71136.715910086.09155.423710106.39179.5827
10136.83198.382110167.07219.348710177.15230.993310187.23237.473610207.35244.7392
10227.41249.331310247.47250.128410277.55242.923910327.59237.584310415.57222.3508
#Mann= 3 , 0 , 0
8628.267  0.0875       08628.267  0.0875       010415.57  0.0875       0
#XS Ineff= 2 , 0
       09654.384        10263.78       0
Bank Sta=8628.267,10415.57
Exp/Cntr=0.3,0.1

Type RM Length L Ch R = 1 ,21161.14,671.863200,671.863200,671.863200
XS GIS Cut Line= 5
696425.202093512 867370.89174971696475.889341682867548.112557516
696488.132709801867594.098010957696554.560000777868244.136501864
696580.599727096869592.994325676
#Sta/Elev= 30
8244.287139.13248738.462133.2714 8828.93128.0763 9140.49125.47189310.522118.5214
9610.578118.29069650.585120.27699750.604117.15389780.609118.76839840.621117.1071
9960.643120.08549970.645117.538410000.65 103.15810010.65107.385110030.66121.7395
10050.66130.109710090.67155.073310140.68 196.04110150.68200.820510190.69 211.349
10210.69219.3147 10250.7228.9886 10280.7246.477610300.71254.286610320.71266.4303
10340.71269.323610390.72294.002910430.73306.579110470.74301.571510478.73303.0915
#Mann= 3 , 0 , 0
8244.287    0.12       08244.287    0.12       010478.73    0.12       0
#XS Ineff= 2 , 0
       09659.031        10331.06       0
Bank Sta=8244.287,10478.73
Exp/Cntr=0.3,0.1

Type RM Length L Ch R = 1 ,20489.28,235.418800,235.418800,235.418800
XS GIS Cut Line= 6
696241.167903098867387.898087063696292.885872704867855.799630048
696256.787711169868257.796567039696127.460819223868747.798381334
 695831.11793739869472.145410224695706.374738413870094.300471427
#Sta/Elev= 30
8599.117133.4182 8979.52132.37979069.592 126.9049390.781123.00819441.552116.5996
9858.861114.10219938.102118.37049978.977113.818210001.6897.9769710025.13113.8425
10198.31111.577710242.02116.6602 10274.8131.017910307.58161.380110340.36176.4829
10394.95217.344310449.22244.889210459.84246.177610485.56234.927610535.46196.0958
10626.12141.607710673.71125.061910753.19134.368410975.37209.635110995.83212.9319
11098.13170.147411169.14182.073911260.44174.4248 11351.2205.861211400.91208.3479
#Mann= 3 , 0 , 0
8599.117   0.109       08599.117   0.109       011400.91   0.109       0
#XS Ineff= 2 , 0
       09933.932        10321.91       0
Bank Sta=8599.117,11400.91
Exp/Cntr=0.3,0.1

Type RM Length L Ch R = 1 ,20253.86,235.418900,235.418900,235.418900
XS GIS Cut Line= 6
696107.006020539867330.722801088696128.689280293867765.679062842
696083.448816994868126.667163128695936.831977966868646.654029958
695661.138230333869404.984894413695538.220868067870044.083050661
#Sta/Elev= 30
8599.103127.89338724.117125.54748874.378128.90329154.723 127.1179225.162122.8237
9336.626123.49459367.126116.38649428.421  114.879666.804113.2958 9833.95114.9607
9970.444111.5821    999999.5456410004.52100.5072 10020.3110.390910031.27111.6685
10253.53108.702710295.97110.168510370.24 131.09810412.69136.721210444.52134.9417
10508.18118.5009 10561.1 111.82110759.71115.959210832.08125.071110975.97171.6444
11016.82178.0751 11088.3184.118511179.55188.070911361.46179.585411400.85 194.135
#Mann= 3 , 0 , 0
8599.103  0.0762       08599.103  0.0762       011400.85  0.0762       0
#XS Ineff= 2 , 0
       09849.631        10356.34       0
Bank Sta=8599.103,11400.85
Exp/Cntr=0.3,0.1

Type RM Length L Ch R = 1 ,20018.44,235.418800,235.418800,235.418800
XS GIS Cut Line= 6
695994.062315915 867260.59714961696009.348438082867672.603401728
695937.448369887868146.504541966695820.437610646868482.447873682
695567.143244507868861.447475345695328.435956559 869919.43496277
#Sta/Elev= 30
 8599.18132.1668 8794.25124.41779357.292123.33439367.459121.26019377.626114.0065
9688.875 111.773 9897.66114.37329973.687108.48499998.486 94.933310010.6698.31707
10022.76 107.11810034.85108.525510360.26105.5909 10475.5165.302910506.75172.1804
10548.42159.787810600.39128.939310631.41115.539210693.46110.884310841.46113.7652
10878.64118.505510909.32128.0218 11001.3176.273811072.51220.130111103.03231.5047
11163.94242.0056 11194.3243.370111265.12231.100111345.96 228.74211400.84215.6013
#Mann= 3 , 0 , 0
 8599.18  0.0623       0 8599.18  0.0623       011400.84  0.0623       0
#XS Ineff= 2 , 0
       09873.063        10448.48       0
Bank Sta=8599.18,11400.84
Exp/Cntr=0.3,0.1

Type RM Length L Ch R = 1 ,19783.02,235.418900,235.418900,235.418900
XS GIS Cut Line= 6
695734.278624378867155.664951832695740.070964476867528.753241933
695701.762676567867848.623580907695485.388470248868591.963139851
695354.592970039869146.476491986695223.624998065869893.054408414
#Sta/Elev= 30
 8599.06132.83779129.402116.6312 9568.03117.79059588.707 110.8989661.078108.1975
 9919.77110.27949974.124107.52179997.90293.3310810021.84106.701410178.28103.5386
10301.35105.236910342.52138.167910435.14202.127210455.73213.267210466.02215.2799
10507.19198.118110589.52145.2005 10620.4128.544310651.23118.066410686.67115.6214
10774.17 119.68510845.67129.890710927.18152.910311008.69186.005811049.24207.8304
11079.65218.008811180.97241.2937 11241.6240.197611292.03223.921311400.91210.6923
#Mann= 3 , 0 , 0
 8599.06   0.057       0 8599.06   0.057       011400.91   0.057       0
#XS Ineff= 2 , 0
       09914.463        10384.74       0
Bank Sta=8599.06,11400.91
Exp/Cntr=0.3,0.1

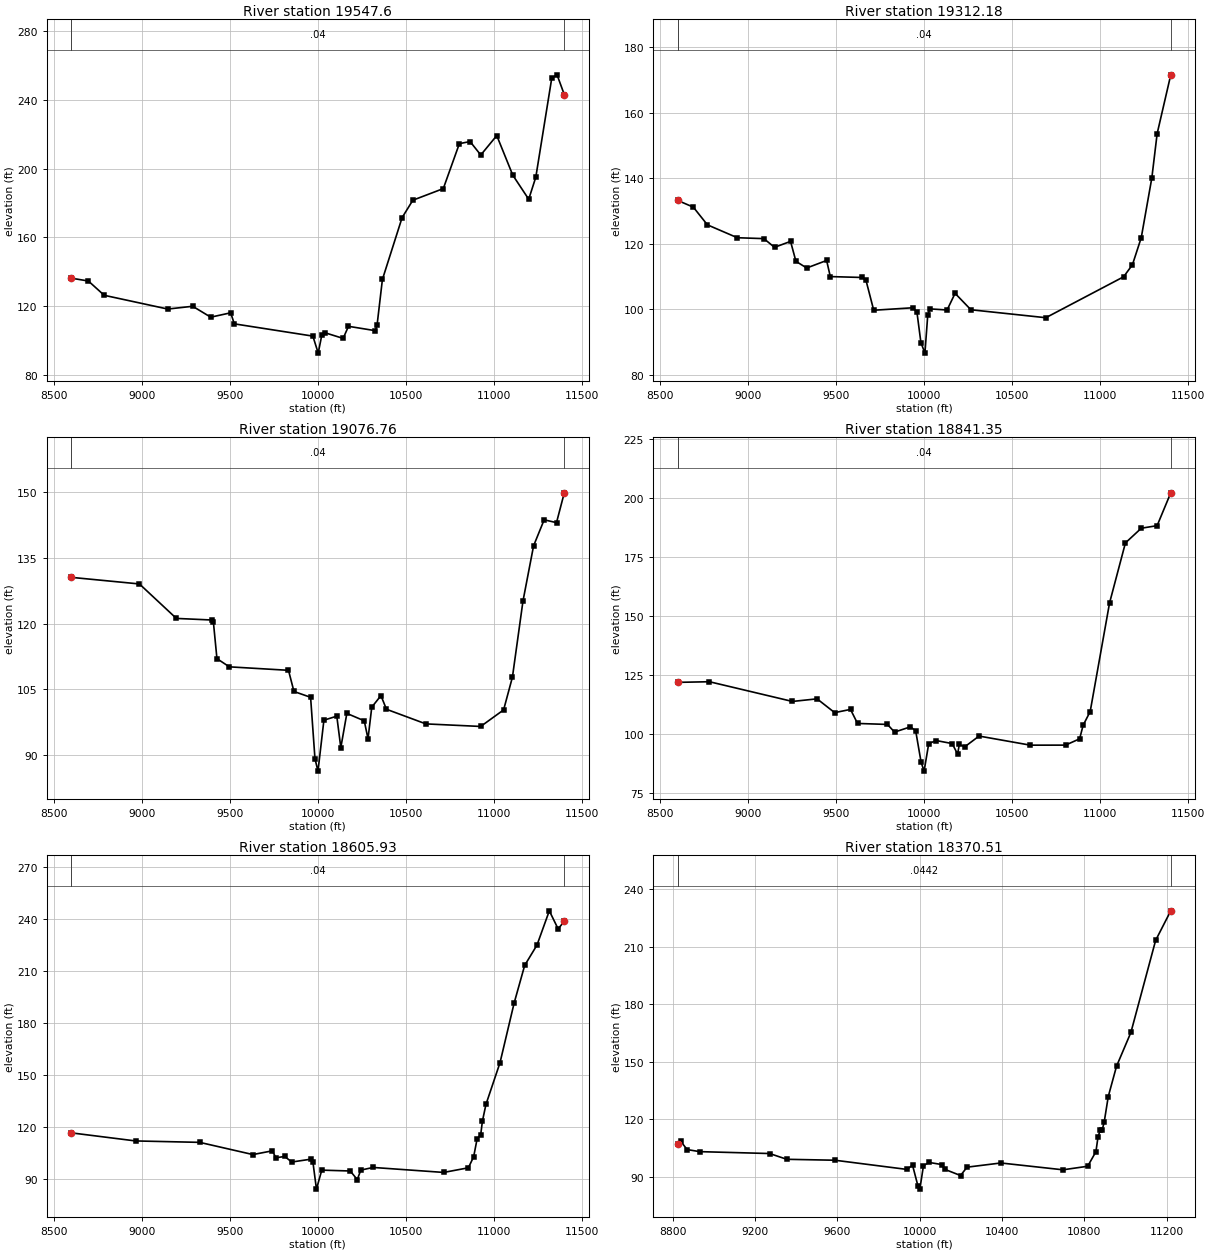
Type RM Length L Ch R = 1 , 19547.6,235.418800,235.418800,235.418800
XS GIS Cut Line= 6
695514.691049607867138.144633889695515.719671688867467.724663225
695491.222778957867710.806299807695298.869322259868478.551059836
695140.433643491869385.830773856695075.251129693869895.895816863
#Sta/Elev= 30
8599.074  136.318696.005 134.6588786.024126.34149147.172118.33639289.065 119.946
9391.449113.60019504.814116.14899525.556109.71389972.045102.578610002.3392.67272
10022.47103.033110042.73104.4777   10144101.245910174.38108.283710326.56105.7506
10336.74108.859510367.28135.569710479.25171.590610540.33181.704110713.33 188.461
10804.65214.631610865.54215.847110926.26208.017311017.21219.330511108.17196.2981
11198.84182.253711239.13195.130611329.71252.761811359.86254.696211400.96243.2017
#Mann= 3 , 0 , 0
8599.074    0.04       08599.074    0.04       011400.96    0.04       0
#XS Ineff= 2 , 0
       09882.274         10176.4       0
Bank Sta=8599.074,11400.96
Exp/Cntr=0.3,0.1

Type RM Length L Ch R = 1 ,19312.18,235.418900,235.418900,235.418900
XS GIS Cut Line= 6
695409.256206329867156.693844418695325.911650461867995.928445294
695229.950843111868249.195653724695039.562262851868522.646942704
694960.596201024868786.216451559694842.113066019869852.181271382
#Sta/Elev= 30
8599.218133.25378687.582131.20748767.588125.8079 8937.73121.8721 9088.38   121.6
 9148.91118.94539240.081 120.7579270.572114.67159331.869112.63039445.065114.9301
9465.919110.0053 9646.25 109.7369668.202108.9842 9712.6999.725979935.076100.4843
9958.37499.12867 9980.8789.8659610003.6786.6304910019.7598.2165210031.94100.1454
10129.6699.8012610175.09104.890210264.8999.8770210690.7597.4457711132.86109.9438
11183.01113.618111233.16121.899411293.34140.162211323.43153.653811400.84171.6233
#Mann= 3 , 0 , 0
8599.218    0.04       08599.218    0.04       011400.84    0.04       0
#XS Ineff= 2 , 0
       09797.478        10171.32       0
Bank Sta=8599.218,11400.84
Exp/Cntr=0.3,0.1

Type RM Length L Ch R = 1 ,19076.76,235.418800,235.418800,235.418800
XS GIS Cut Line= 6
695101.898965072866899.309785493695133.879972113867383.201690033
695111.459438564867780.730008354695039.160526824868153.686444846
694832.711778748868759.269177317694756.271782051869649.146516756
#Sta/Elev= 30
8599.065130.58978986.126129.0816 9196.17121.19869396.555 120.8379406.605120.3255
9426.705112.00249497.112110.12419833.333109.3296 9864.38104.48819958.976103.1584
9983.80589.10965   1000186.2738410034.5897.9239710107.8498.8453810130.6991.64418
10164.9699.4770910263.9397.7818710285.2793.6635110306.61100.901410358.78103.5449
10390.08100.419410614.1597.0760410925.5296.4909111055.87100.274711105.98107.7657
 11166.1125.202311226.23137.801111286.36143.7564 11356.5143.100311400.74149.9219
#Mann= 3 , 0 , 0
8599.065    0.04       08599.065    0.04       011400.74    0.04       0
#XS Ineff= 2 , 0
       09924.698        10372.49       0
Bank Sta=8599.065,11400.74
Exp/Cntr=0.3,0.1

Type RM Length L Ch R = 1 ,18841.35,235.418900,235.418900,235.418900
XS GIS Cut Line= 6
694740.436916469866956.628037244694795.915888005867501.559946673
694821.756864383 868294.21924098694793.195887863868379.349635166
 694729.81009316868775.068776525694682.965841771869742.441270713
#Sta/Elev= 30
 8599.11121.89798778.997122.16229250.548113.80239390.676114.90889490.688109.0584
9580.699110.42389620.704104.47439790.768104.05759830.845100.80829921.007103.0248
 9951.06101.3903 9981.9388.06819    999984.2611610025.2495.9147610067.4197.22927
10158.6395.9437210189.1891.5062310199.3695.5534710229.9194.5640710311.3799.12951
10602.6395.2697610802.8495.2862110882.9297.9543110902.94103.726210942.98109.5349
11053.09155.588211143.18181.013111233.27 187.24111323.36188.329911400.88202.2499
#Mann= 3 , 0 , 0
 8599.11    0.04       0 8599.11    0.04       011400.88    0.04       0
#XS Ineff= 2 , 0
       09736.072        10266.35       0
Bank Sta=8599.11,11400.88
Exp/Cntr=0.3,0.1

Type RM Length L Ch R = 1 ,18605.93,235.418800,235.418800,235.418800
XS GIS Cut Line= 6
694439.157548415866914.275490575694606.471414013868092.939250177
694605.842136451868234.439009147694574.280310624868487.851502416
694611.363359687869037.564304938694601.035008377869700.031463757
#Sta/Elev= 30
8599.055116.44188964.626111.77799328.408110.96179631.115103.91219741.713106.0696
9761.783 102.0439811.893102.82719851.91399.602199962.149 101.2759972.20499.61992
9992.31483.9574710022.5994.9247310184.3394.4260510224.3789.48539 10244.494.95102
10314.6896.4737110715.73 93.596610855.7496.2720210885.75102.627910905.75113.1184
10925.75115.336910935.75123.297210955.75132.870811035.76157.017611115.78191.3523
11175.81213.125711245.84 224.88311315.86244.638311365.88234.210111400.93238.5755
#Mann= 3 , 0 , 0
8599.055    0.04       08599.055    0.04       011400.93    0.04       0
#XS Ineff= 2 , 0
       09672.665        10356.24       0
Bank Sta=8599.055,11400.93
Exp/Cntr=0.3,0.1

Type RM Length L Ch R = 1 ,18370.51,551.000000,551.000000,551.000000
XS GIS Cut Line= 6
693960.763206609867300.768989816694191.526409715868098.243393198
694458.314115971868420.534121796 694534.88925752868595.571354911
694585.806707799868973.453233719694589.274251968869538.407759219
#Sta/Elev= 30
 8825.41107.25858839.965108.53598870.647104.23528932.011103.15949271.528102.1713
9354.67199.168159588.41798.683919938.45893.889979965.25796.131019991.13585.45371
10000.8883.6262810018.3395.8186510045.2297.5405610109.6796.3884710121.4593.96208
 10198.490.7149510229.9495.0673410394.1797.2511710695.7193.6950810815.7995.54093
10855.79103.123610865.79110.662810875.79114.173910885.79114.298610895.79118.4294
 10915.8 131.886 10955.8147.6227 11025.8165.312611145.81213.237911219.24228.6309
#Mann= 3 , 0 , 0
 8825.41  0.0442       0 8825.41  0.0442       011219.24  0.0442       0
#XS Ineff= 2 , 0
       09317.411        10364.24       0
Bank Sta=8825.41,11219.24
Exp/Cntr=0.3,0.1

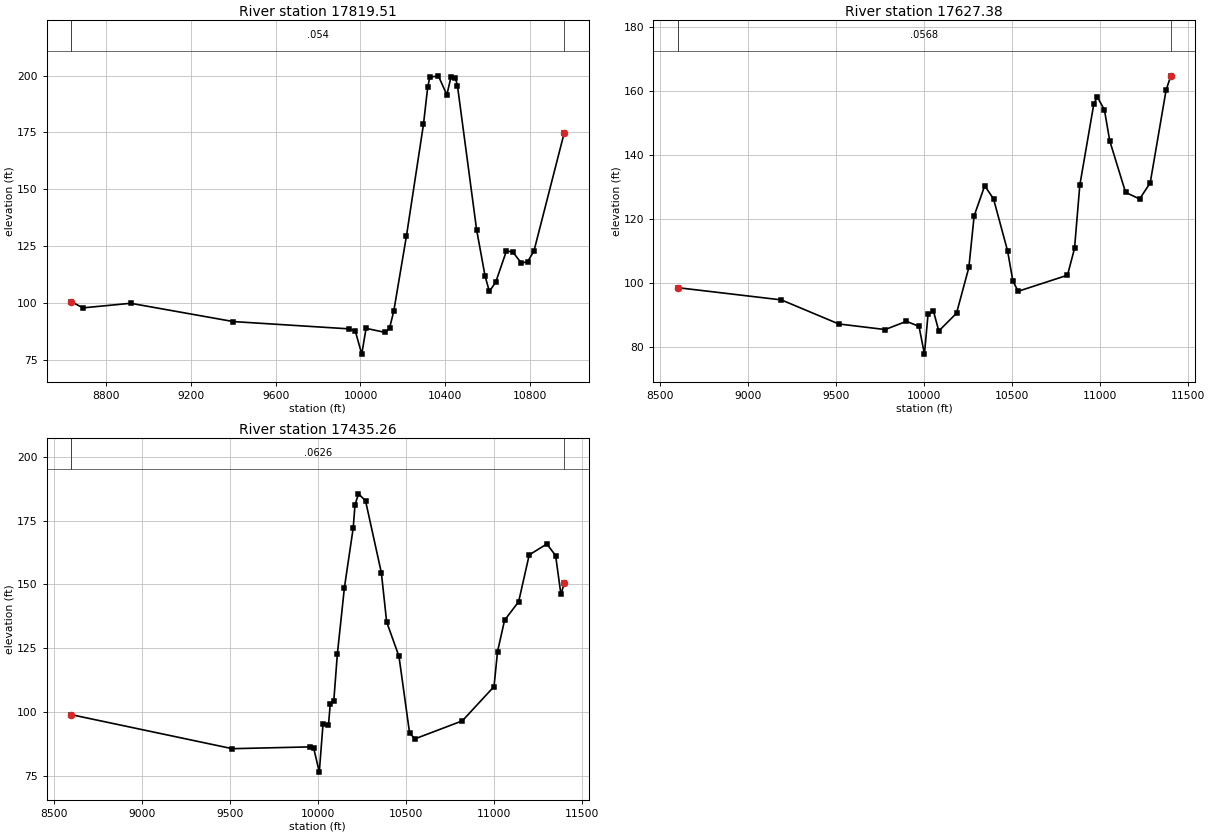
Type RM Length L Ch R = 1 ,17819.51,192.124600,192.124600,192.124600
XS GIS Cut Line= 6
693687.559068959867300.768989816693798.807255805867819.461068451
693970.123784602 868475.33404775693972.443441004 868563.81759128
693947.665340424868809.207677737693990.624123812869588.082982615
#Sta/Elev= 30
8636.284100.61458691.51397.923588916.19699.932949400.34791.899399945.00688.70492
9975.29787.8433810005.9377.5990410026.3888.92455 10116.987.13574 10136.988.95795
 10156.996.4600410216.94 129.59410297.05178.5481 10317.1194.965510327.12199.2338
10367.21199.8577 10407.3 191.51710427.35199.538510447.39198.990210457.41195.4262
10547.62 132.25510587.71 111.82910607.76105.140910637.82109.228510687.89122.8384
10717.93122.559410757.97 117.63510788.01118.171910818.05122.900710961.23174.9566
#Mann= 3 , 0 , 0
8636.284   0.054       08636.284   0.054       010961.23   0.054       0
#XS Ineff= 2 , 0
       09113.272        10349.51       0
Bank Sta=8636.284,10961.23
Exp/Cntr=0.3,0.1

Type RM Length L Ch R = 1 ,17627.38,192.124500,192.124500,192.124500
XS GIS Cut Line= 6
693515.612692933867237.338425294693692.999341168868136.995120529
693752.798653054868519.738742064693795.462641231868738.060583237
 693825.41633804869304.676421753693840.911167416 870011.97252286
#Sta/Elev= 30
8599.02798.54291  9187.594.731799513.98387.220319777.41485.477869898.65888.04645
 9970.0486.4615510000.8477.8091810021.3390.2360810052.07 91.232410082.4585.03488
10183.1990.5642210253.34104.8542 10283.4  120.9610343.47130.345110393.51126.2539
10473.59109.981310503.62100.590710533.6597.4225410813.86102.432310853.88110.7854
10883.89130.517410963.93155.990810983.93158.017311023.94153.989511053.94144.3844
11143.96128.277111223.97 126.22311283.98131.240211373.99160.096111400.96164.6455
#Mann= 3 , 0 , 0
8599.027  0.0568       08599.027  0.0568       011400.96  0.0568       0
#XS Ineff= 2 , 0
       09220.335        10271.17       0
Bank Sta=8599.027,11400.96
Exp/Cntr=0.3,0.1

Type RM Length L Ch R = 1 ,17435.26,192.124600,192.124600,192.124600
XS GIS Cut Line= 6
693425.996200862867273.692857446693569.388794163868089.465584606
  693608.9826607868442.782045764 693608.80105025868586.880339507
693560.626069362868879.521152842693581.141798309870054.468442053
#Sta/Elev= 30
8599.124 98.85619513.889 85.51829955.82286.22349 9976.46 85.782110008.3976.32364
10029.67 95.235710060.4494.61544 10070.7103.028910090.86104.323810110.99 122.558
10151.18148.686610201.22172.106810211.23181.124110231.24185.479510271.24182.7515
10361.24154.496710391.25135.227910461.27121.732410521.2891.7889510551.2989.35787
10821.3796.43672 11001.4109.8871 11021.4123.6059 11061.4 135.90111141.41143.1696
11201.42161.526911301.43165.800911351.43161.288811381.43146.1345 11400.9150.3479
#Mann= 3 , 0 , 0
8599.124  0.0626       08599.124  0.0626       0 11400.9  0.0626       0
#XS Ineff= 2 , 0
       09233.511        10102.54       0
Bank Sta=8599.124,11400.9
Exp/Cntr=0.3,0.1