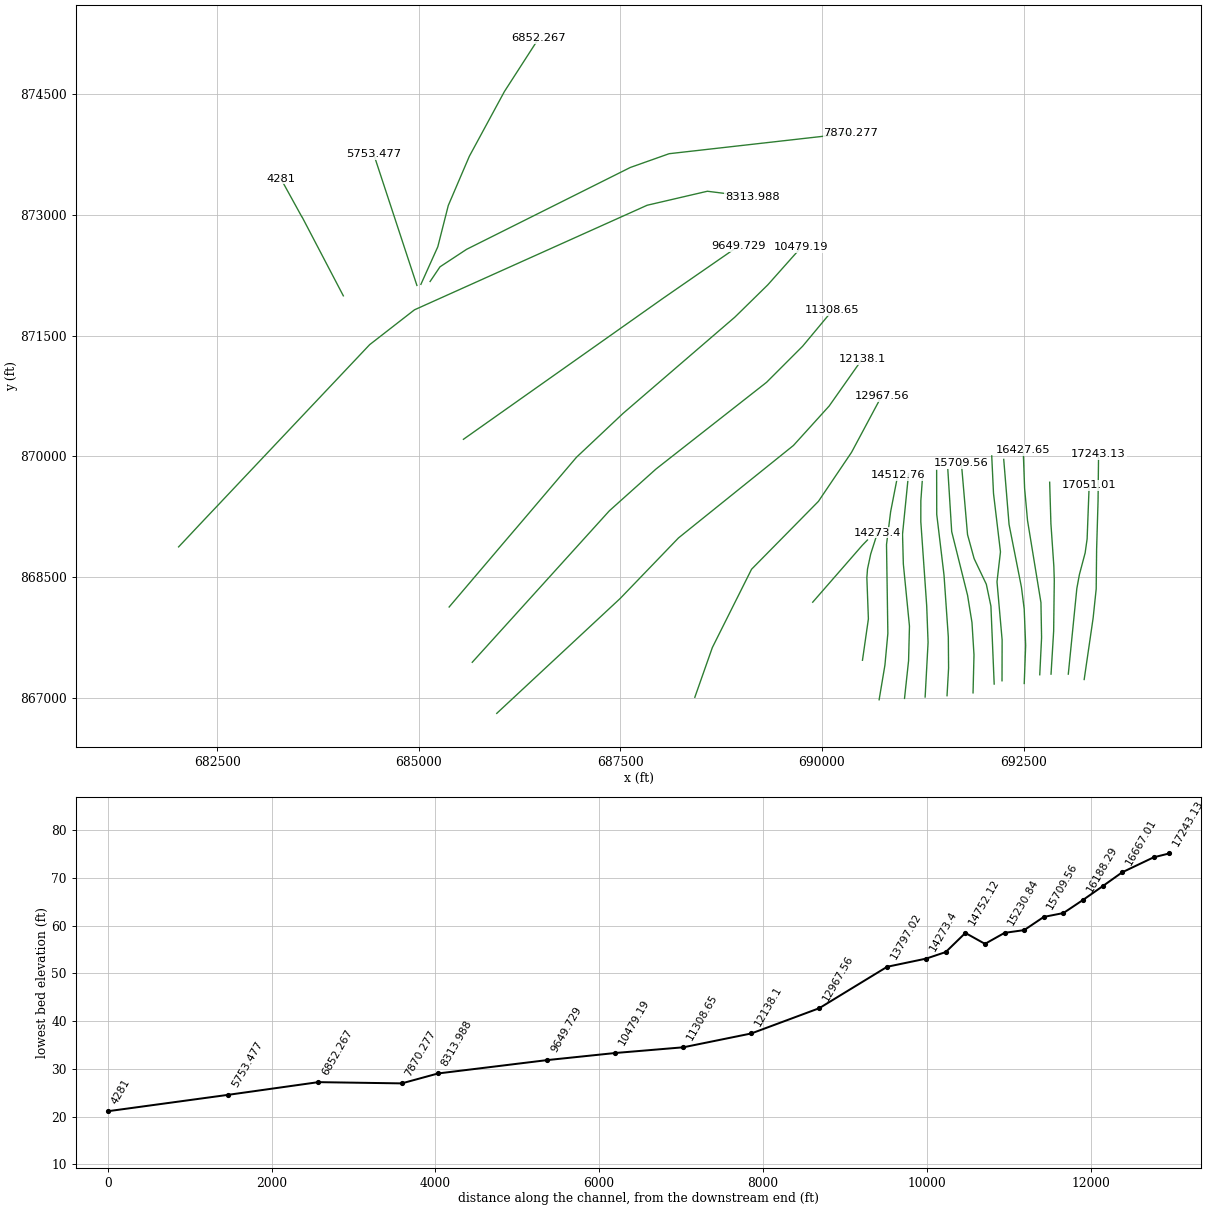
HEC-RAS study 13600_ras.prj: 13600

--- 13600_ras.g01 (geometry) --- (continued)

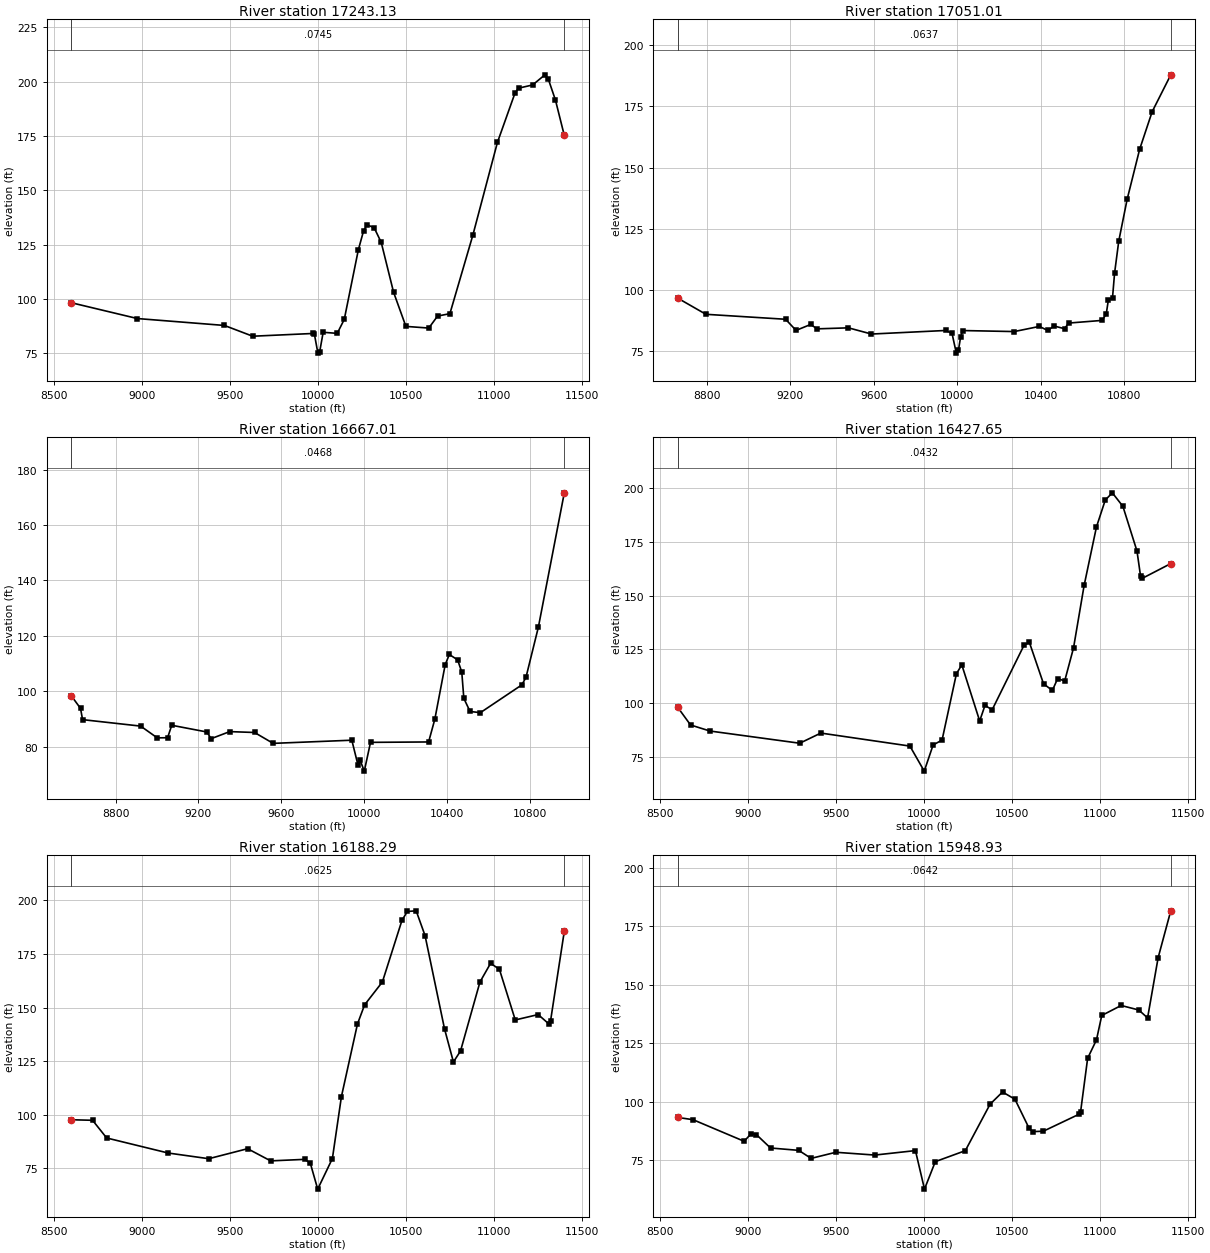
Type RM Length L Ch R = 1 ,17243.13,192.124600,192.124600,192.124600
XS GIS Cut Line= 6
 693251.54021119867233.774141237693362.335120106867994.306673046
693400.497844461868355.819910731 693405.80969463868849.457957262
693423.610895896869447.651875926693429.925975951870025.205305348
#Sta/Elev= 30
8599.03798.262948974.42690.991149469.03587.818619629.98482.861229970.443 84.1173
9980.44683.8615310000.4575.0841510010.4675.6293610030.4684.6696910110.4684.17348
10150.4690.6239610230.47122.642910260.49131.4382 10280.5 134.12210320.52132.7207
10360.55125.986510430.59   103.110500.6387.3833910630.6986.61198 10680.792.13428
10750.7293.2340710880.74 129.21611020.75171.994111120.76194.726611140.76196.9614
11220.76198.439911290.77203.101411310.77200.974811350.77191.442611400.98175.2005
#Mann= 3 , 0 , 0
8599.037  0.0745       08599.037  0.0745       011400.98  0.0745       0
#XS Ineff= 2 , 0
       09370.412        10182.52       0
Bank Sta=8599.037,11400.98
Exp/Cntr=0.3,0.1

Type RM Length L Ch R = 1 ,17051.01,384.000000,384.000000,384.000000
XS GIS Cut Line= 6
693054.597985953867300.768508039693160.484208614868362.957239702
693192.350459248868535.663823664693263.566611469868804.073402658
693288.031195015868977.620197788693313.467584997869644.272567749
#Sta/Elev= 30
8661.02796.695368796.01290.11099 9177.8588.087249228.05783.548969298.34685.97324
9328.46984.170799479.089 84.58819589.617  82.0569944.78683.507629975.73782.35977
9996.37174.2668810006.66 75.493810017.0580.8954810027.4783.4822310274.1183.06602
10394.7885.1675110434.8883.5059110464.9685.3401110515.06 84.232110535.0886.53567
 10695.287.62001 10715.290.2520510725.21 95.872610745.2196.8564610755.22106.9717
10775.22120.021510815.23136.977910875.25157.438610935.27172.787111024.56187.8447
#Mann= 3 , 0 , 0
8661.027  0.0637       08661.027  0.0637       011024.56  0.0637       0
#XS Ineff= 2 , 0
       0  9485.1        10256.62       0
Bank Sta=8661.027,11024.56
Exp/Cntr=0.3,0.1

Type RM Length L Ch R = 1 ,16667.01,239.361400,239.361400,239.361400
XS GIS Cut Line= 6
692840.500325251867300.768989816692872.952050954867833.956939086
692880.829599082868465.051949516692875.228441834868640.985292286
692838.989396334869166.937811792692823.526104301869680.252927929
#Sta/Elev= 30
8585.74198.329368630.15393.798838640.19489.726858920.81887.39159 9000.92 83.1494
9050.96483.193299070.98287.691429241.07385.263519261.081 82.84269351.08785.40312
9471.09585.088389561.10281.158929941.264 82.29919971.35773.220679981.38875.05559
10001.4571.1316910031.5581.5227210312.2981.6670810342.3489.8879510392.42109.5788
10412.45113.259610452.51111.309410472.52106.912810482.53 97.400910512.5592.67345
10562.5892.2530410762.72102.278210782.74104.982410842.76123.161510968.02171.6409
#Mann= 3 , 0 , 0
8585.741  0.0468       08585.741  0.0468       010968.02  0.0468       0
#XS Ineff= 2 , 0
       09472.504        10379.08       0
Bank Sta=8585.741,10968.02
Exp/Cntr=0.3,0.1

Type RM Length L Ch R = 1 ,16427.65,239.361400,239.361400,239.361400
XS GIS Cut Line= 6
 692700.65464725867292.580389293692723.242703389867753.619108247
692715.359430793868187.980880269692548.896397563869206.155003054
692512.617196091869606.073282694692495.483742673870077.031116836
#Sta/Elev= 30
8599.09697.901448671.67889.715988781.92386.895849292.13381.210019412.19385.94278
 9918.3779.885129999.79468.2142410050.16 80.383110101.1482.7019210182.72113.5947
10213.31 117.72210314.84  91.58910345.1998.8567310385.5696.7484310567.06126.8852
10597.22128.225110677.66108.921310727.87105.789210757.97111.3163 10798.1110.2321
10848.26125.631610908.45154.709810978.59181.970611028.66194.505811068.72197.8623
11128.81191.576311208.86170.751111228.87159.282311238.87158.016711400.92164.8981
#Mann= 3 , 0 , 0
8599.096  0.0432       08599.096  0.0432       011400.92  0.0432       0
#XS Ineff= 2 , 0
       09471.234           10239       0
Bank Sta=8599.096,11400.92
Exp/Cntr=0.3,0.1

Type RM Length L Ch R = 1 ,16188.29,239.361500,239.361500,239.361500
XS GIS Cut Line= 6
692508.146015402867184.427812642692525.821350441867656.635479835
692507.733746021868107.524046914692473.382082894868379.387374946
692319.978695183869156.582469407692253.838619922 869963.44566861
#Sta/Elev= 30
8599.061 97.70828719.85497.458418799.96989.205949150.05582.18022 9380.21 79.5372
 9600.98 84.20989732.04278.522589925.90279.234869957.14377.500559999.39365.34592
10082.8779.6245410134.17108.515510225.39 142.38510265.94151.310410367.02161.9941
10478.16190.693710508.47194.861210558.99195.169710609.46183.621110720.28140.0535
10770.66124.657410810.96129.753610921.53 161.96610981.81170.666711031.95167.9228
11122.17144.265411252.39146.779611312.45142.460411322.45143.670211400.92185.6677
#Mann= 3 , 0 , 0
8599.061  0.0625       08599.061  0.0625       011400.92  0.0625       0
#XS Ineff= 2 , 0
       09680.494        10142.95       0
Bank Sta=8599.061,11400.92
Exp/Cntr=0.3,0.1

Type RM Length L Ch R = 1 ,15948.93,239.361400,239.361400,239.361400
XS GIS Cut Line= 6
692232.560022694867218.112035842692233.996334494867724.680109971
692170.327640106868445.713373356692213.297575968868816.891046954
692127.024876931 869541.68895816692105.072114024870006.798406204
#Sta/Elev= 30
8599.07293.255958686.01792.290368976.07883.068029016.09486.311979046.10685.89479
9126.17180.191459286.50179.181419356.76875.748799497.476 78.36279718.847 77.1707
9949.77879.0816410001.21 62.605610062.6774.3583210233.28 79.052310374.1298.93607
10444.77104.137210515.41101.033710596.15 88.559610616.3387.1912210676.8887.37524
10878.14 94.5756 10888.295.5679610928.43118.550110978.58126.414211008.66136.8534
11118.94141.128411219.06139.199211269.09 135.812 11329.1161.560611400.91181.6005
#Mann= 3 , 0 , 0
8599.072  0.0642       08599.072  0.0642       011400.91  0.0642       0
#XS Ineff= 2 , 0
       09876.727        10150.95       0
Bank Sta=8599.072,11400.91
Exp/Cntr=0.3,0.1

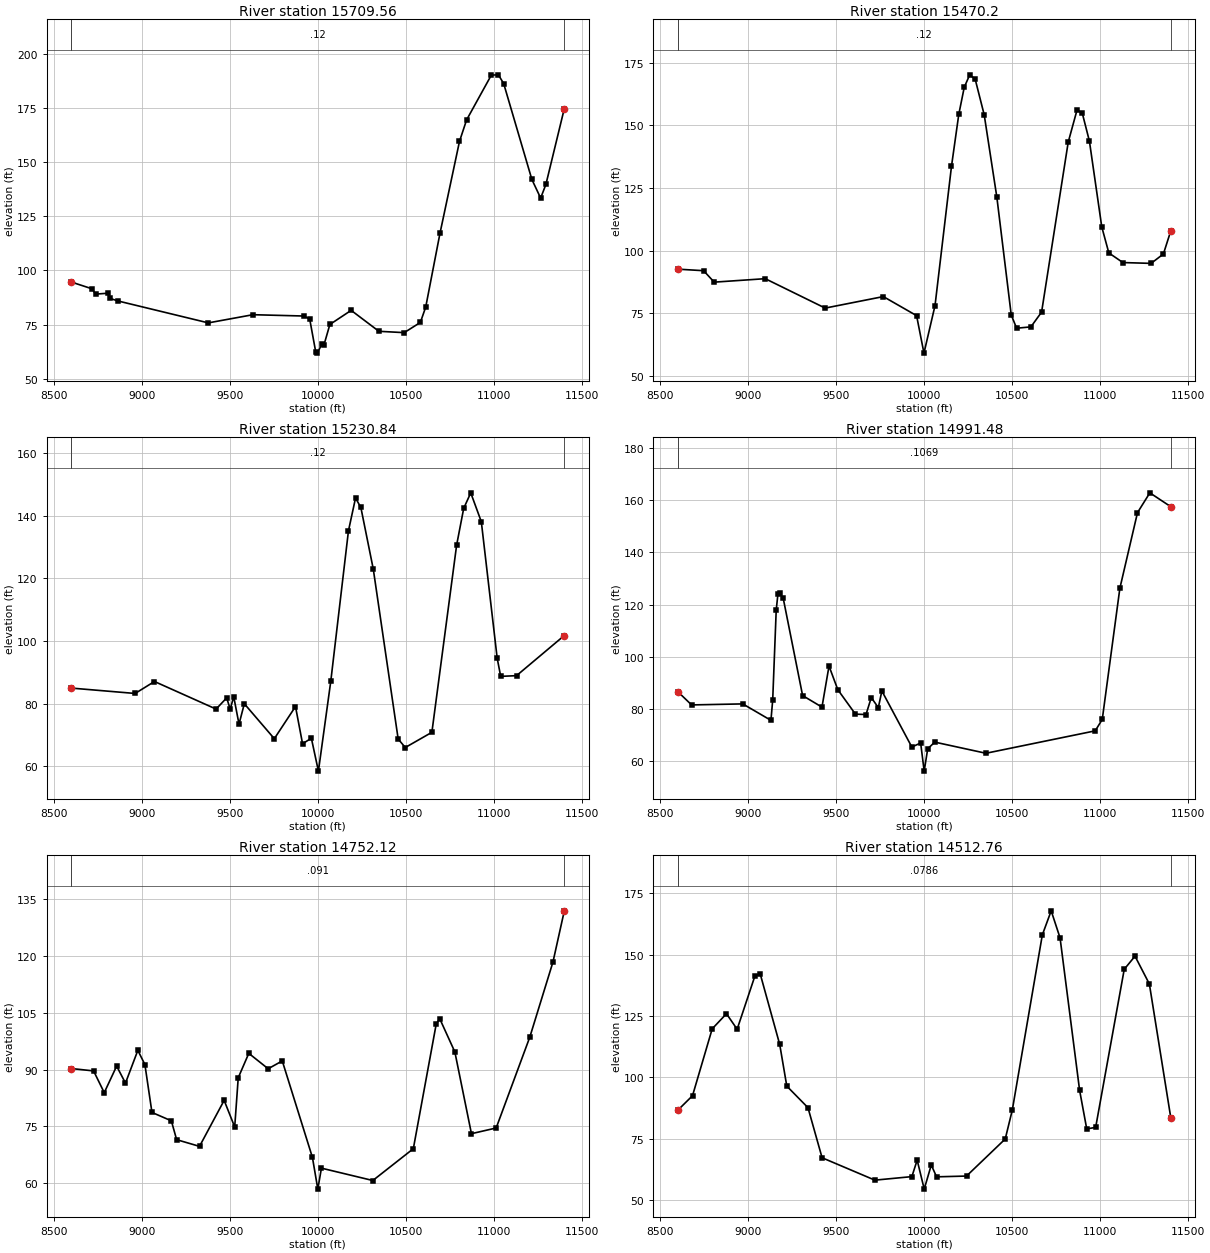
Type RM Length L Ch R = 1 ,15709.56,239.361400,239.361400,239.361400
XS GIS Cut Line= 6
692135.490189453867177.271514909692094.898720953868144.374730811
692038.065861018868414.775305139691886.589568617 868733.33571338
691804.815316963869031.581803696691728.491226452869919.473780348
#Sta/Elev= 30
8599.06194.601938716.87691.47493 8736.8989.022078806.906 89.43828816.90787.09304
8866.91285.811129377.74375.753219631.35879.525979920.47778.918269953.93477.50542
9988.15962.334639997.48661.7951510022.7565.9402210034.2865.36546 10068.575.02487
10189.5281.5319110347.2271.8674410491.0871.2493310582.75 75.956610613.2783.05038
10694.21 117.05310805.19 159.50110845.46169.394610986.15190.093811026.24190.2206
 11056.3186.203311216.46141.959811266.47133.336111296.47139.695411400.95174.6449
#Mann= 3 , 0 , 0
8599.061    0.12       08599.061    0.12       011400.95    0.12       0
#XS Ineff= 2 , 0
       09894.935         10139.6       0
Bank Sta=8599.061,11400.95
Exp/Cntr=0.3,0.1

Type RM Length L Ch R = 1 , 15470.2,239.361400,239.361400,239.361400
XS GIS Cut Line= 6
691873.229191016867068.354976785691885.061595617867539.245317091
691860.133716699867940.128405534691805.417019957868277.847899523
691608.557813484869067.796812703691560.525857836869836.960916062
#Sta/Elev= 30
8599.062 92.56448745.91591.956068805.96387.38032    909688.765189436.74177.02263
9767.25381.615339956.29674.008449998.17959.0377910061.0578.0286310154.65 133.648
10196.07154.372210227.13 165.18310258.19170.167310289.25168.439810340.59154.1952
10412.33121.368410494.1774.3130410524.6668.9847510605.9569.51802 10666.775.41283
10818.04143.279710868.27 156.16310898.38154.754710938.53143.683411008.78109.4326
11048.8499.0522511128.9295.2002311288.9594.8780211358.9698.6194311400.94107.8517
#Mann= 3 , 0 , 0
8599.062    0.12       08599.062    0.12       011400.94    0.12       0
#XS Ineff= 2 , 0
       09910.714        10110.65       0
Bank Sta=8599.062,11400.94
Exp/Cntr=0.3,0.1

Type RM Length L Ch R = 1 ,15230.84,239.361400,239.361400,239.361400
XS GIS Cut Line= 6
691550.728945387 867032.96609463691569.976147593867374.696389077
 691566.59896319867761.934831902691513.278137956868527.905787735
691423.001491769869282.454868064691421.853111917869826.408533723
#Sta/Elev= 30
8599.03884.983558961.65283.267679071.65787.087179421.86678.280499481.95981.85965
9502.00978.262149522.07282.232099552.16673.46479 9582.2679.985939752.79268.82024
9873.16879.094099913.26767.207729963.37968.9682810003.41 58.461210073.5787.11402
10174.14135.210710214.39145.690410244.64142.671110315.33 122.956 10456.768.71532
 10497.166.0038610648.3170.86162   10789 130.66710829.11142.380610869.21147.3491
10929.27138.116911019.3794.5495411039.3888.7299111129.3988.9506711400.96101.7739
#Mann= 3 , 0 , 0
8599.038    0.12       08599.038    0.12       011400.96    0.12       0
#XS Ineff= 2 , 0
       0 9862.36        10094.92       0
Bank Sta=8599.038,11400.96
Exp/Cntr=0.3,0.1

Type RM Length L Ch R = 1 ,14991.48,239.361500,239.361500,239.361500
XS GIS Cut Line= 6
691279.125490119867016.889416497691315.612140525867692.912054976
691298.609496496868146.983261237691225.532765979869192.350027281
691225.936427135869449.795603147691251.810614569 869813.42608008
#Sta/Elev= 30
8599.03786.618378677.532 81.52588968.40681.916949128.49875.619979138.50283.37627
9158.502117.87559168.503124.20939178.503124.34259198.503122.31889308.51385.10949
9418.54180.684049458.551 96.4195 9508.5887.357399608.711 77.99689668.78977.83762
9698.82984.335759738.88680.489899758.92586.877159929.25865.394559979.382 66.9417
9999.43956.1588910019.4964.71277 10059.667.2739410350.5563.0036210971.5371.59315
11011.5475.9642411111.61126.2205 11211.8155.200611282.02162.790411400.98157.4772
#Mann= 3 , 0 , 0
8599.037  0.1069       08599.037  0.1069       011400.98  0.1069       0
#XS Ineff= 2 , 0
       09859.134        10190.95       0
Bank Sta=8599.037,11400.98
Exp/Cntr=0.3,0.1

Type RM Length L Ch R = 1 ,14752.12,239.361400,239.361400,239.361400
XS GIS Cut Line= 6
691023.545808748866999.450401001691073.866052866867468.109034138
691084.763498669867895.296263693691008.869510974868666.046496393
690998.820424862869036.011278184691073.961291041869788.700996454
#Sta/Elev= 30
 8599.0690.311938725.698 89.68038786.21983.930598856.62290.951948906.86986.46143
8977.10495.113229017.238 91.36369057.37278.712829167.56476.493339197.58771.51359
9327.65669.742769467.66581.893639527.68274.856899547.69387.868049607.727 94.3239
9717.84190.25088 9798.0392.323839969.39666.8185410000.0558.4439710020.5463.98641
10312.6360.7216410542.83 69.124510672.85102.046910692.86103.486110778.8494.69988
10873.1273.0957211013.6574.60028   1120598.6346911336.45118.462611400.95131.9842
#Mann= 3 , 0 , 0
 8599.06   0.091       0 8599.06   0.091       011400.95   0.091       0
#XS Ineff= 2 , 0
       09871.237        10231.16       0
Bank Sta=8599.06,11400.95
Exp/Cntr=0.3,0.1

Type RM Length L Ch R = 1 ,14512.76,239.361400,239.361400,239.361400
XS GIS Cut Line= 6
690708.564347832866982.661135441690780.667013152867413.492960781
690816.901755478867805.480111797690800.139273696868907.051567708
690851.115030408869313.685196219690938.881874174869763.911742407
#Sta/Elev= 30
8599.042 86.60978682.86892.54961 8794.67119.81168875.733125.96398936.382119.6373
9037.458141.37239067.688142.15449178.383113.44039218.59396.458089338.99587.65589
9419.185 67.23939719.28458.109679929.53759.550639959.58966.286599999.65954.44898
10039.7364.2931310069.7859.46244   1024059.7794810460.1174.8983710500.1786.67239
10670.92158.100910721.23167.9187 10771.7156.882310882.7994.7374210923.2879.01244
   1097479.62032 11136.5144.097711197.66149.4351 11279.3138.088611400.9583.57357
#Mann= 3 , 0 , 0
8599.042  0.0786       08599.042  0.0786       011400.95  0.0786       0
#XS Ineff= 2 , 0
       09728.928        10172.13       0
Bank Sta=8599.042,11400.95
Exp/Cntr=0.3,0.1

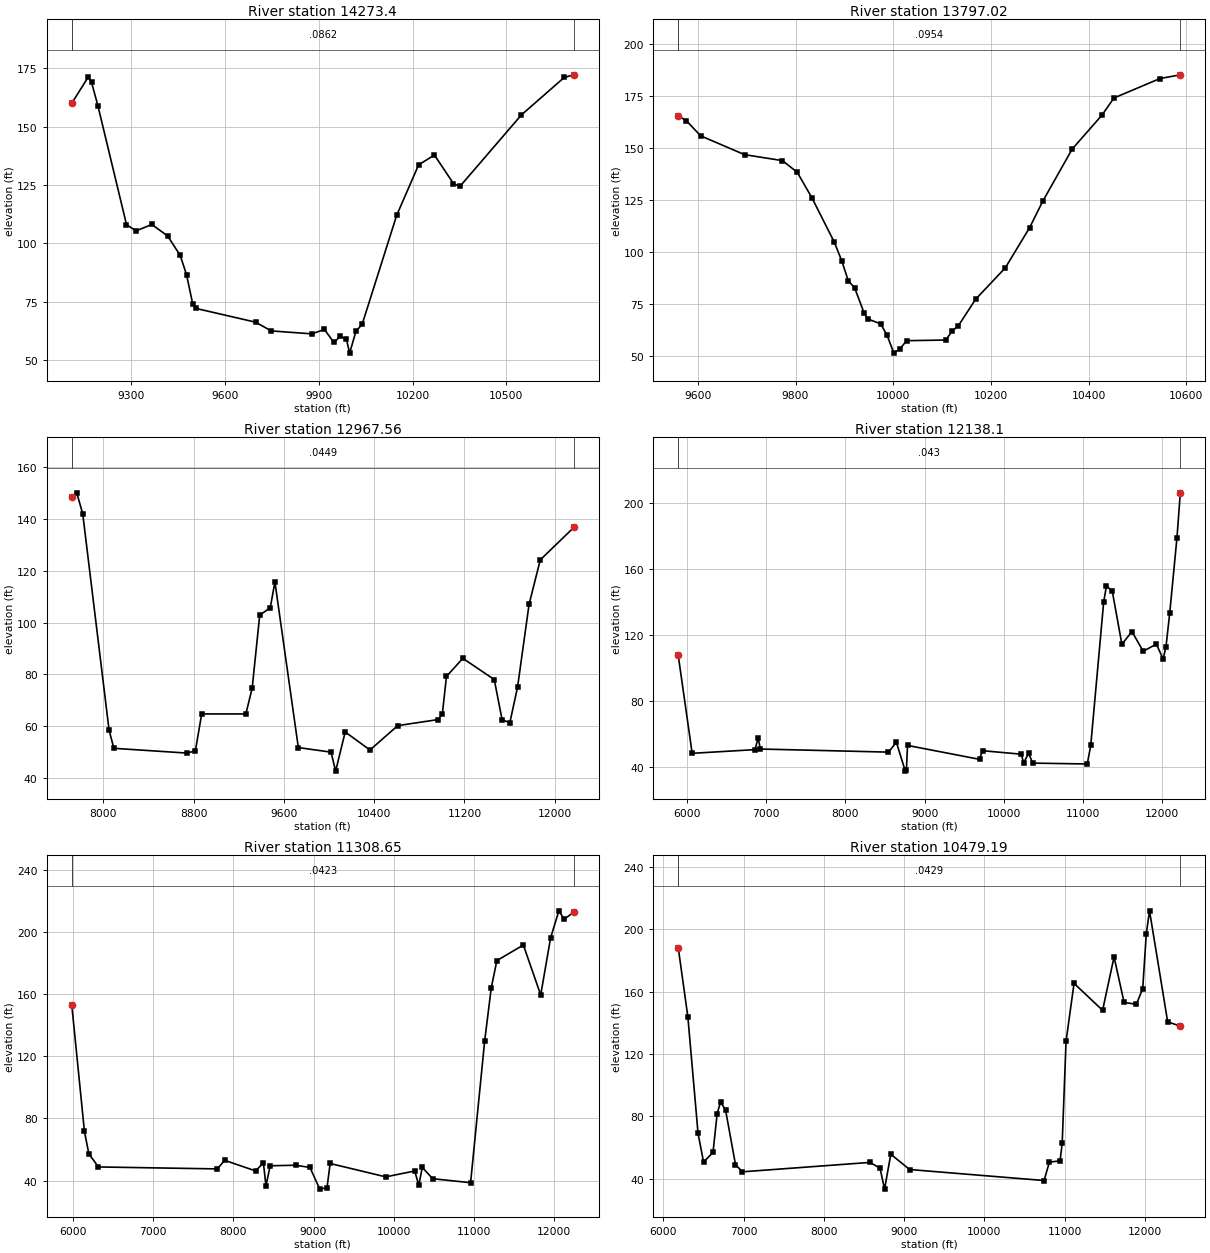
Type RM Length L Ch R = 1 , 14273.4,476.375600,476.375600,476.375600
XS GIS Cut Line= 6
690502.047898298867472.776341661 690575.45326966867984.751397237
690556.432073265868496.506907716690564.498580456868604.072746232
690604.304122686868791.002805024690688.362260044869053.686253503
#Sta/Elev= 30
9110.334159.96359163.475171.31499173.637168.88889193.962158.86639285.341108.0761
9315.709105.37479366.321108.11019416.785103.21759457.11194.882519477.27486.65125
9497.43673.922059507.51872.196999698.17166.311589748.22162.577499878.28261.32015
 9918.3963.206649948.52857.623999968.66260.219579988.796 58.97099998.86353.07321
10018.9862.3582310039.0965.4635510149.38112.033610219.58133.629210270.02137.8298
10331.07125.5981 10351.5124.385510548.39 155.00310685.45171.047110715.93172.1382
#Mann= 3 , 0 , 0
9110.334  0.0862       09110.334  0.0862       010715.93  0.0862       0
#XS Ineff= 2 , 0
       09620.998        10103.92       0
Bank Sta=9110.334,10715.93
Exp/Cntr=0.3,0.1

Type RM Length L Ch R = 1 ,13797.02,829.458100,829.458100,829.458100
XS GIS Cut Line= 3
689884.895688603868192.667265991690500.390473425868898.549396813
690564.052013108868964.140074054
#Sta/Elev= 30
 9559.82165.49979576.182163.22829605.627155.90459695.591146.83549773.003143.9734
9803.435138.37279833.867125.94179879.515104.66589894.73195.687979907.87386.23325
9921.14182.683659940.37970.659839947.67667.810169974.21165.461419987.479 59.8868
10001.2451.3640510014.01 53.423710027.28 57.348410107.7657.6672810120.1661.84912
10133.4264.5541210168.6277.2550510229.4892.4071510279.37111.7848 10305.9124.3381
10366.43149.534110427.29 165.83410451.85174.084810546.05183.435510587.76185.2342
#Mann= 3 , 0 , 0
 9559.82  0.0954       0 9559.82  0.0954       010587.76  0.0954       0
#XS Ineff= 2 , 0
       0                10194.92       0
Bank Sta=9559.82,10587.76
Exp/Cntr=0.3,0.1

Type RM Length L Ch R = 1 ,12967.56,829.458100,829.458100,829.458100
XS GIS Cut Line= 6
 688423.04958415867013.450737998688640.063472986867629.770182431
689126.337321788868601.135498717689955.367593527869442.524228886
690366.578390241870051.398511052690739.295669854870748.227092266
#Sta/Elev= 30
7720.184148.69537764.233150.13277817.242142.03638050.48258.606938092.88951.50206
8742.04449.658258815.58250.520018871.49764.781069262.90464.76771 9318.8274.72873
9385.918102.97469479.012105.71959520.415115.74079727.94551.7890710017.8850.02222
10058.3642.6940410143.1857.8011710362.9850.8469510608.8260.26469 10967.262.59558
11004.4164.8876611040.77 79.275911185.7686.2271611464.1178.0578311533.3262.60854
11601.9961.3349711670.6575.1414111772.71107.104211871.97124.268912169.45136.7731
#Mann= 3 , 0 , 0
7720.184  0.0449       07720.184  0.0449       012169.45  0.0449       0
#XS Ineff= 2 , 0
       09725.115        10401.72       0
Bank Sta=7720.184,12169.45
Exp/Cntr=0.3,0.1

Type RM Length L Ch R = 1 , 12138.1,829.458100,829.458100,829.458100
XS GIS Cut Line= 6
685966.452361912866813.797960207687496.212461621868237.753910318
688220.539066404868989.765354365 689646.12849912870136.451770172
690088.977118552 870625.44332701690498.125472426871206.550516427
#Sta/Elev= 30
5890.815107.59496066.435 48.20736858.82150.436546899.80757.53899 6927.1350.81017
8544.52148.935388644.13454.931218756.75937.410828770.69937.860278784.63952.99171
9693.53344.569569731.17449.7934710219.4147.6852710250.7742.4837810313.6248.24162
10364.4642.2688111053.5941.7464611097.3452.9972211260.86140.008211295.25149.5904
11368.37146.692811490.48114.292311617.33122.057511759.07110.099811926.09 114.386
12011.11105.309412047.04112.792812094.77133.515412185.46178.806712227.86206.1286
#Mann= 3 , 0 , 0
5890.815   0.043       05890.815   0.043       012227.86   0.043       0
#XS Ineff= 2 , 0
       09757.098        10305.95       0
Bank Sta=5890.815,12227.86
Exp/Cntr=0.3,0.1

Type RM Length L Ch R = 1 ,11308.65,829.458100,829.458100,829.458100
XS GIS Cut Line= 6
685662.632917434867447.478515774687362.271011412869325.205661133
 687942.40710789869844.952164382689312.127162337870919.057107896
689758.847368807871365.925261348 690130.04420644871811.669017524
#Sta/Elev= 30
5982.717152.98546140.48771.755466196.10157.191896316.00848.787617799.85147.52995
7890.138 53.05848277.285  46.2318374.27851.431618406.20936.646828458.96149.55074
8776.36249.893428955.53648.458129077.55334.519919168.171 35.45389207.19551.01703
9900.95842.4120210262.97 46.202210313.1736.9741810357.2848.4601810487.1641.23333
   10960 38.639311135.52129.783111218.37164.168111288.07181.5875 11618.7191.5944
11835.18159.455411958.26196.149112061.69213.605812127.64208.258312248.65212.7117
#Mann= 3 , 0 , 0
5982.717  0.0423       05982.717  0.0423       012248.65  0.0423       0
#XS Ineff= 2 , 0
       09636.673        10260.15       0
Bank Sta=5982.717,12248.65
Exp/Cntr=0.3,0.1

Type RM Length L Ch R = 1 ,10479.19,829.458100,829.458100,829.458100
XS GIS Cut Line= 6
 685376.17458418868133.242404655686954.667521238869989.352964967
687532.213688076870533.385302052688920.621351004871728.829421133
689326.908518344872127.247413784689743.307273149872595.000931442
#Sta/Elev= 30
6183.886188.20226303.694143.89646430.89669.067076499.54950.720586617.06156.82628
6669.28981.819796710.83889.116026773.04784.253136897.46649.109396982.65744.43079
8573.40150.464168699.22346.766658755.62233.327698833.45855.688819068.13245.90487
10744.0538.8402210810.4950.6425610943.3951.4691810969.9762.6926211017.93128.1154
 11117.6165.325411473.51148.047111616.51182.274211741.67153.078211895.21151.9332
11973.82162.016312018.21197.195512058.56211.8655 12284.8 140.65312442.34137.8745
#Mann= 3 , 0 , 0
6183.886  0.0429       06183.886  0.0429       012442.34  0.0429       0
#XS Ineff= 2 , 0
       09652.742        10273.22       0
Bank Sta=6183.886,12442.34
Exp/Cntr=0.3,0.1

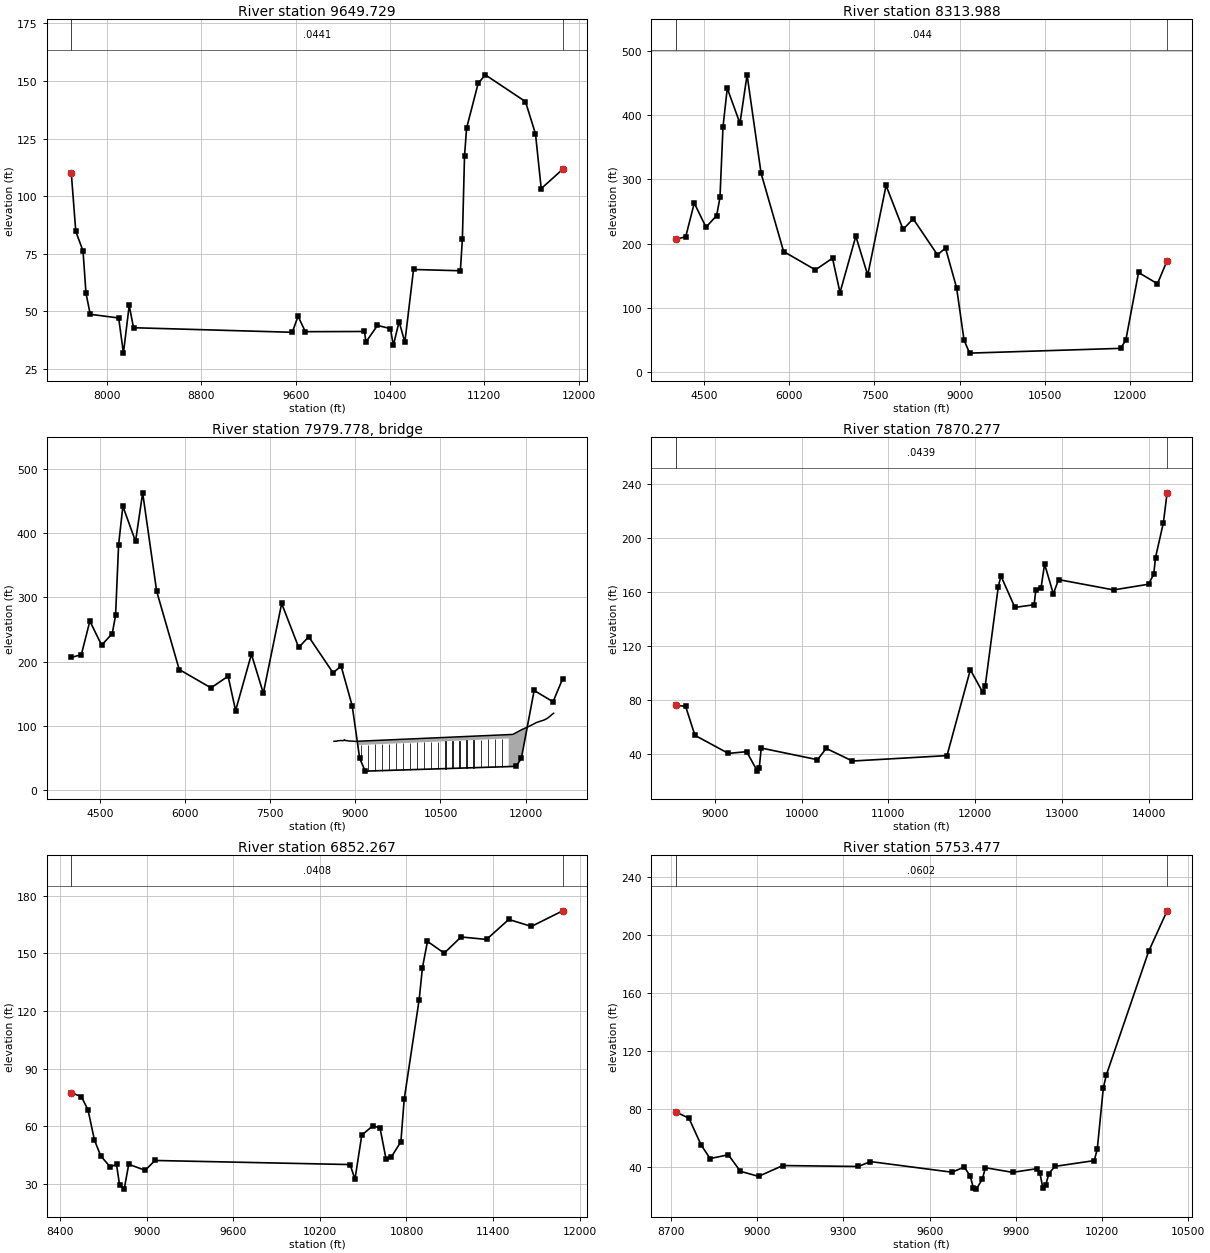
Type RM Length L Ch R = 1 ,9649.729,1335.741900,1335.741900,1335.741900
XS GIS Cut Line= 3
 685553.44671759870212.884103164688036.085606456871966.356325388
688964.905050904872608.717436492
#Sta/Elev= 30
 7696.47110.2782  7735.184.677957796.31476.228377821.47557.901337857.52848.70464
8098.81647.122518139.11131.847628188.08252.537688224.81142.880649571.51440.89739
9620.48547.896499681.69941.1579910183.6541.2476810196.2136.6877510293.8443.85821
10404.0242.5131210428.5135.2052610477.4845.5132210526.4536.6040810599.91  68.176
10997.2367.6143411014.2381.3856111032.39117.451611049.97129.549611147.97148.9971
11208.77152.700811549.21 141.07411634.31127.083911682.95103.288211865.21 111.688
#Mann= 3 , 0 , 0
 7696.47  0.0441       0 7696.47  0.0441       011865.21  0.0441       0
#XS Ineff= 2 , 0
       09613.195         10298.7       0
Bank Sta=7696.47,11865.21
Exp/Cntr=0.3,0.1

Type RM Length L Ch R = 1 ,8313.988,443.710800,443.710800,443.710800
XS GIS Cut Line= 6
 682020.90065098868878.511328171684390.524586827871386.606830746
684946.156617552 871818.56051673687831.913130879873115.420656607
 688578.44090867873289.031767726689133.996464252873219.587323278
#Sta/Elev= 30
 3998.78 206.4434176.395210.73264326.877263.17664533.504225.47974720.663243.7274
4779.322 271.8684832.563382.24044907.729442.31415131.116387.52135256.461463.2589
    5503309.6635 5899.78187.60696459.107158.96236760.642177.10556892.656123.5105
7171.228211.43827380.841150.65467704.036290.60098003.755222.01528180.331238.7154
8608.805182.39188750.266193.00358946.136130.75989076.71549.27806 9174.6529.04577
 11832.136.48686 11924.549.13291 12149.3154.877912481.87137.239912652.18173.3353
#Mann= 3 , 0 , 0
 3998.78   0.044       0 3998.78   0.044       012652.18   0.044       0
#XS Ineff= 2 , 0
       09646.947        10291.37       0
Bank Sta=3998.78,12652.18
Exp/Cntr=0.3,0.1

Type RM Length L Ch R = 3 ,7979.778,,,
BEGIN DESCRIPTION:
END DESCRIPTION:
Bridge Culvert--1,0,-1,-1, 0
Deck Dist Width WeirC Skew NumUp NumDn MinLoCord MaxHiCord MaxSubmerge Is_Ogee
144.855400,154.000000,2.6,0, 60, 60, , , 0.95, 0, 0,0,,
 8625.72 8630.70 8641.92 8653.13 8675.56 8697.98 8709.20 8745.58 8776.47 8787.69
 8798.90 8810.11 8811.90 8821.32 8854.96 8877.39 8888.60 8900.32 8911.03 8933.45
 8955.88 8975.93 8975.93 9000.73 9023.16 9034.37 9054.1111700.9311700.9311771.60
11818.4911928.9211958.9411988.9611998.9712008.9712028.9812038.9912048.9912059.00
12069.0012079.0112089.0212119.0312149.0512159.0512179.0612189.0712199.0812219.09
12249.1012269.1112299.1312329.1512369.1712389.1812429.2012469.2212479.2312492.94
   75.53   75.47   75.76   75.70   75.83   76.59   76.50   76.79   76.56   76.84
   76.78   78.04   77.78   76.79   76.59   76.15   76.14   75.90   76.00   75.84
   75.86   75.68   75.68   75.38   75.53   75.49   75.70   86.02   86.02   86.30
   88.37   93.72   94.85   96.11   96.39   96.87   97.64   98.13   98.43   98.84
   99.34   99.71  100.24  101.54  103.00  103.38  104.45  104.82  105.07  105.80
  106.61  107.30  108.01  109.03  110.83  111.94  114.70  117.89  118.45  119.39
 -924.47 -924.53 -924.24 -924.30 -924.17 -923.41 -923.50 -923.21 -923.44 -923.16
 -923.22 -921.96 -922.22 -923.21 -923.41 -923.85 -923.86 -924.10 -924.00 -924.16
 -924.14 -924.32   69.68   69.38   69.53   69.49   69.70   80.02 -913.98 -913.70
 -911.63 -906.28 -905.15 -903.89 -903.61 -903.13 -902.36 -901.87 -901.57 -901.16
 -900.66 -900.29 -899.76 -898.46 -897.00 -896.62 -895.55 -895.18 -894.93 -894.20
 -893.39 -892.70 -891.99 -890.97 -889.17 -888.06 -885.30 -882.11 -881.55 -880.61
 8625.72 8630.70 8641.92 8653.13 8675.56 8697.98 8709.20 8745.58 8776.47 8787.69
 8798.90 8810.11 8811.90 8821.32 8854.96 8877.39 8888.60 8900.32 8911.03 8933.45
 8955.88 9000.73 9023.16 9034.37 9054.11 9083.04 9083.0411771.6011808.0411808.04
11828.5311928.9211958.9411988.9611998.9712008.9712028.9812038.9912048.9912059.00
12069.0012119.0312149.0512159.0512179.0612189.0712199.0812219.0912249.1012269.11
12299.1312329.1512359.1612369.1712389.1812409.1912429.2012469.2212479.2312492.94
   75.53   75.47   75.76   75.70   75.83   76.59   76.50   76.79   76.56   76.84
   76.78   78.04   77.78   76.79   76.59   76.15   76.14   75.90   76.00   75.84
   75.86   75.38   75.53   75.49   75.70   75.81   75.81   86.30   87.93   87.93
   88.85   93.72   94.85   96.11   96.39   96.87   97.64   98.13   98.43   98.84
   99.34  101.54  103.00  103.38  104.45  104.82  105.07  105.80  106.61  107.30
  108.01  109.03  110.36  110.83  111.94  113.27  114.70  117.89  118.45  119.39
 -924.47 -924.53 -924.24 -924.30 -924.17 -923.41 -923.50 -923.21 -923.44 -923.16
 -923.22 -921.96 -922.22 -923.21 -923.41 -923.85 -923.86 -924.10 -924.00 -924.16
 -924.14 -924.62 -924.47 -924.51 -924.30 -924.19   69.81   80.30   81.93 -912.07
 -911.15 -906.28 -905.15 -903.89 -903.61 -903.13 -902.36 -901.87 -901.57 -901.16
 -900.66 -898.46 -897.00 -896.62 -895.55 -895.18 -894.93 -894.20 -893.39 -892.70
 -891.99 -890.97 -889.64 -889.17 -888.06 -886.73 -885.30 -882.11 -881.55 -880.61
Pier Skew, UpSta & Num, DnSta & Num=  ,9097.98, 2 ,9205.09, 2 , 0 , 0 , 0 ,,
    4.00    4.00
 -924.13   75.87
    4.00    4.00
 -923.71   76.29
Pier Skew, UpSta & Num, DnSta & Num=  ,9222.02, 2 ,9329.14, 2 , 0 , 0 , 0 ,,
    4.00    4.00
 -923.65   76.35
    4.00    4.00
 -923.23   76.77
Pier Skew, UpSta & Num, DnSta & Num=  ,9346.07, 2 ,9453.18, 2 , 0 , 0 , 0 ,,
    4.00    4.00
 -923.16   76.84
    4.00    4.00
 -922.75   77.25
Pier Skew, UpSta & Num, DnSta & Num=  ,9470.11, 2 ,9577.23, 2 , 0 , 0 , 0 ,,
    4.00    4.00
 -922.68   77.32
    4.00    4.00
 -922.26   77.74
Pier Skew, UpSta & Num, DnSta & Num=  ,9594.16, 2 ,9701.27, 2 , 0 , 0 , 0 ,,
    4.00    4.00
 -922.20   77.80
    4.00    4.00
 -921.78   78.22
Pier Skew, UpSta & Num, DnSta & Num=  ,9718.20, 2 ,9825.32, 2 , 0 , 0 , 0 ,,
    4.00    4.00
 -921.71   78.29
    4.00    4.00
 -921.29   78.71
Pier Skew, UpSta & Num, DnSta & Num=  ,9842.25, 2 ,9949.36, 2 , 0 , 0 , 0 ,,
    4.00    4.00
 -921.23   78.77
    4.00    4.00
 -920.81   79.19
Pier Skew, UpSta & Num, DnSta & Num=  ,9966.30, 2 ,10073.41, 2 , 0 , 0 , 0 ,,
    4.00    4.00
 -920.74   79.26
    4.00    4.00
 -920.33   79.67
Pier Skew, UpSta & Num, DnSta & Num=  ,10090.34, 2 ,10197.45, 2 , 0 , 0 , 0 ,,
    4.00    4.00
 -920.26   79.74
    4.00    4.00
 -919.84   80.16
Pier Skew, UpSta & Num, DnSta & Num=  ,10214.39, 2 ,10321.50, 2 , 0 , 0 , 0 ,,
    4.00    4.00
 -919.78   80.22
    4.00    4.00
 -919.36   80.64
Pier Skew, UpSta & Num, DnSta & Num=  ,10338.43, 2 ,10445.54, 2 , 0 , 0 , 0 ,,
    4.00    4.00
 -919.29   80.71
    4.00    4.00
 -918.87   81.13
Pier Skew, UpSta & Num, DnSta & Num=  ,10462.48, 2 ,10569.59, 2 , 0 , 0 , 0 ,,
    4.00    4.00
 -918.81   81.19
    4.00    4.00
 -918.39   81.61
Pier Skew, UpSta & Num, DnSta & Num=  ,10586.52, 2 ,10693.64, 2 , 0 , 0 , 0 ,,
    4.00    4.00
 -918.32   81.68
    4.00    4.00
 -917.91   82.09
Pier Skew, UpSta & Num, DnSta & Num=  ,10710.57, 2 ,10817.68, 2 , 0 , 0 , 0 ,,
    4.00    4.00
 -917.84   82.16
    4.00    4.00
 -917.42   82.58
Pier Skew, UpSta & Num, DnSta & Num=  ,10834.61, 2 ,10941.73, 2 , 0 , 0 , 0 ,,
    4.00    4.00
 -917.36   82.64
    4.00    4.00
 -916.94   83.06
Pier Skew, UpSta & Num, DnSta & Num=  ,10958.66, 2 ,11065.77, 2 , 0 , 0 , 0 ,,
    4.00    4.00
 -916.87   83.13
    4.00    4.00
 -916.45   83.55
Pier Skew, UpSta & Num, DnSta & Num=  ,11082.70, 2 ,11189.82, 2 , 0 , 0 , 0 ,,
    4.00    4.00
 -916.39   83.61
    4.00    4.00
 -915.97   84.03
Pier Skew, UpSta & Num, DnSta & Num=  ,11206.75, 2 ,11313.86, 2 , 0 , 0 , 0 ,,
    4.00    4.00
 -915.90   84.10
    4.00    4.00
 -915.49   84.51
Pier Skew, UpSta & Num, DnSta & Num=  ,11330.80, 2 ,11437.91, 2 , 0 , 0 , 0 ,,
    4.00    4.00
 -915.42   84.58
    4.00    4.00
 -915.00   85.00
Pier Skew, UpSta & Num, DnSta & Num=  ,11454.84, 2 ,11561.95, 2 , 0 , 0 , 0 ,,
    4.00    4.00
 -914.94   85.06
    4.00    4.00
 -914.52   85.48
Pier Skew, UpSta & Num, DnSta & Num=  ,11578.89, 2 ,11686.00, 2 , 0 , 0 , 0 ,,
    4.00    4.00
 -914.45   85.55
    4.00    4.00
 -914.03   85.97
BR Coef=-1 , 0 , 0 ,, 0 ,,,0.8,0,1,0,
WSPro=,,,, 1 ,,,, 0 ,,,, 0 ,,,,-1 ,-1 ,-1 , 0 , 0 , 0 , 0 , 0
BC Design=,, 0 ,, 0 ,,,,,,

Type RM Length L Ch R = 1 ,7870.277,1018.009700,1018.009700,1018.009700
XS GIS Cut Line= 6
685139.934743553872169.918959484685262.468686461872351.531767726
685592.329797596872568.545656621687623.579797626873584.170656621
688104.639504969873754.672831416690357.954797596 874009.51787883
#Sta/Elev= 30
8548.05375.781618662.75275.033448770.16753.514829155.53240.106119366.215 41.3955
9489.46526.967779511.55929.452729534.18744.0790610182.3835.43154   1028343.81855
10584.8734.4532511674.9438.4734611943.73102.125412084.6385.5965112114.82 90.0182
12265.77163.766912295.97171.695812456.99148.340912678.39150.331312698.52161.1258
 12758.9163.039812799.15180.554712899.79158.404512960.17168.963213594.19161.3233
13996.74165.527814057.12172.981714077.25185.334114167.82211.007514211.05233.2966
#Mann= 3 , 0 , 0
8548.053  0.0439       08548.053  0.0439       014211.05  0.0439       0
#XS Ineff= 2 , 0
       09590.806        10280.63       0
Bank Sta=8548.053,14211.05
Exp/Cntr=0.3,0.1

Type RM Length L Ch R = 1 ,6852.267,1098.790200,1098.790200,1098.790200
XS GIS Cut Line= 6
685025.899986518872134.405432993685235.463382115872600.413745541
685365.504069365873112.751037984685626.236843527873722.041135133
686061.110294025874524.908808375686487.065750771875185.373877597
#Sta/Elev= 30
8477.89977.485088548.73975.290858594.08468.436058638.80552.700058682.499 44.5175
8747.94638.761918791.42340.15756 8812.8329.287438844.58827.227658876.17740.15194
8990.02337.023349057.79342.1403210409.4340.0144310443.1432.3637110490.2155.33822
10567.8760.2398210616.8458.9984910658.7242.7142410692.7843.7022710761.1451.89225
10784.0473.9869210887.52125.746210910.52142.5286 10945.3156.166611061.24 150.063
11178.02158.482411354.15157.1873 11508.6167.599311665.18163.972911881.97172.0827
#Mann= 3 , 0 , 0
8477.899  0.0408       08477.899  0.0408       011881.97  0.0408       0
#XS Ineff= 2 , 0
       09400.742        10558.68       0
Bank Sta=8477.899,11881.97
Exp/Cntr=0.3,0.1

Type RM Length L Ch R = 1 ,5753.477,1472.476900,1472.476900,1472.476900
XS GIS Cut Line= 2
684976.289933383872120.886907667684441.567711145873745.886907652
#Sta/Elev= 30
8715.81677.969568762.25673.516748804.36655.104268835.94845.667148899.11348.31514
8941.22336.897849004.388 33.39219088.60840.859129351.79540.223049393.90543.59397
9678.14836.249359720.25839.842289741.31333.59307 9751.8425.550189762.36724.57889
9783.42231.51439 9793.95 39.36429888.69736.169039972.917 38.69069983.44535.99369
9993.97225.36527 10004.527.7553310015.0335.3564710036.0840.2918310172.9444.27717
10183.47 52.285610204.5294.5424610215.05103.476510362.43188.869110426.53 216.781
#Mann= 3 , 0 , 0
8715.816  0.0602       08715.816  0.0602       010426.53  0.0602       0
#XS Ineff= 2 , 0
       09672.928                       0
Bank Sta=8715.816,10426.53
Exp/Cntr=0.3,0.1

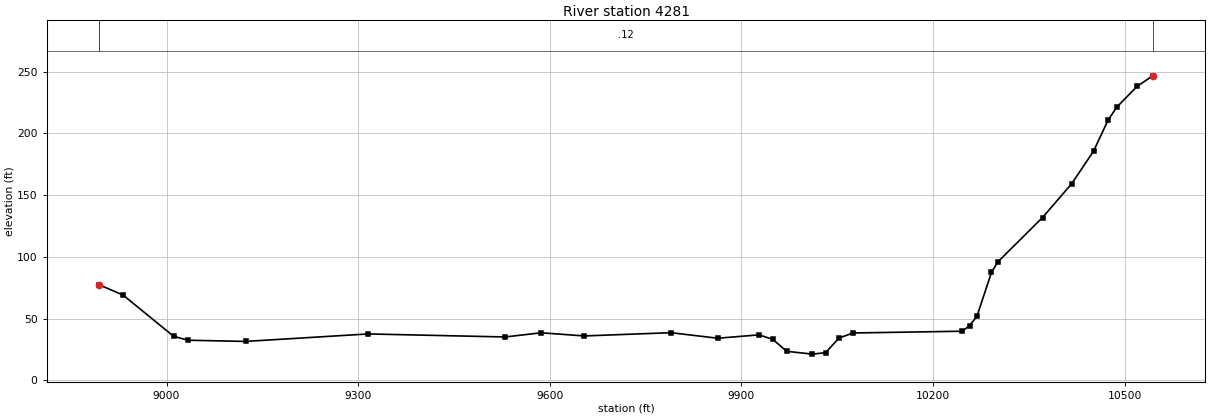
Type RM Length L Ch R = 1 ,    4281,0.000000,0.000000,0.000000
XS GIS Cut Line= 4
684063.870821357871992.040962249 683551.99280256872970.481490105
683549.993754268872970.419797167683287.923712537873446.189039738
#Sta/Elev= 30
8894.75177.217978931.94869.008079010.94935.632549033.521 32.40629123.80731.43965
9315.66637.499379530.09635.047479586.52538.42626 9654.2435.883599789.66938.51155
9863.07834.026539927.795  36.7549949.36833.04107 9970.9423.4324310011.3521.14125
10032.0822.34472 10052.834.1696310074.7338.2769610245.9839.70444 10257.444.28682
10268.8151.7266610291.6587.3152510301.5295.8060110371.56131.848610417.23159.2086
10451.48185.633810474.32210.875310488.05221.396510519.98238.243810544.17246.6589
#Mann= 3 , 0 , 0
8894.751    0.12       08894.751    0.12       010544.17    0.12       0
#XS Ineff= 2 , 0
       09238.453                       0
Bank Sta=8894.751,10544.17
Exp/Cntr=0.3,0.1